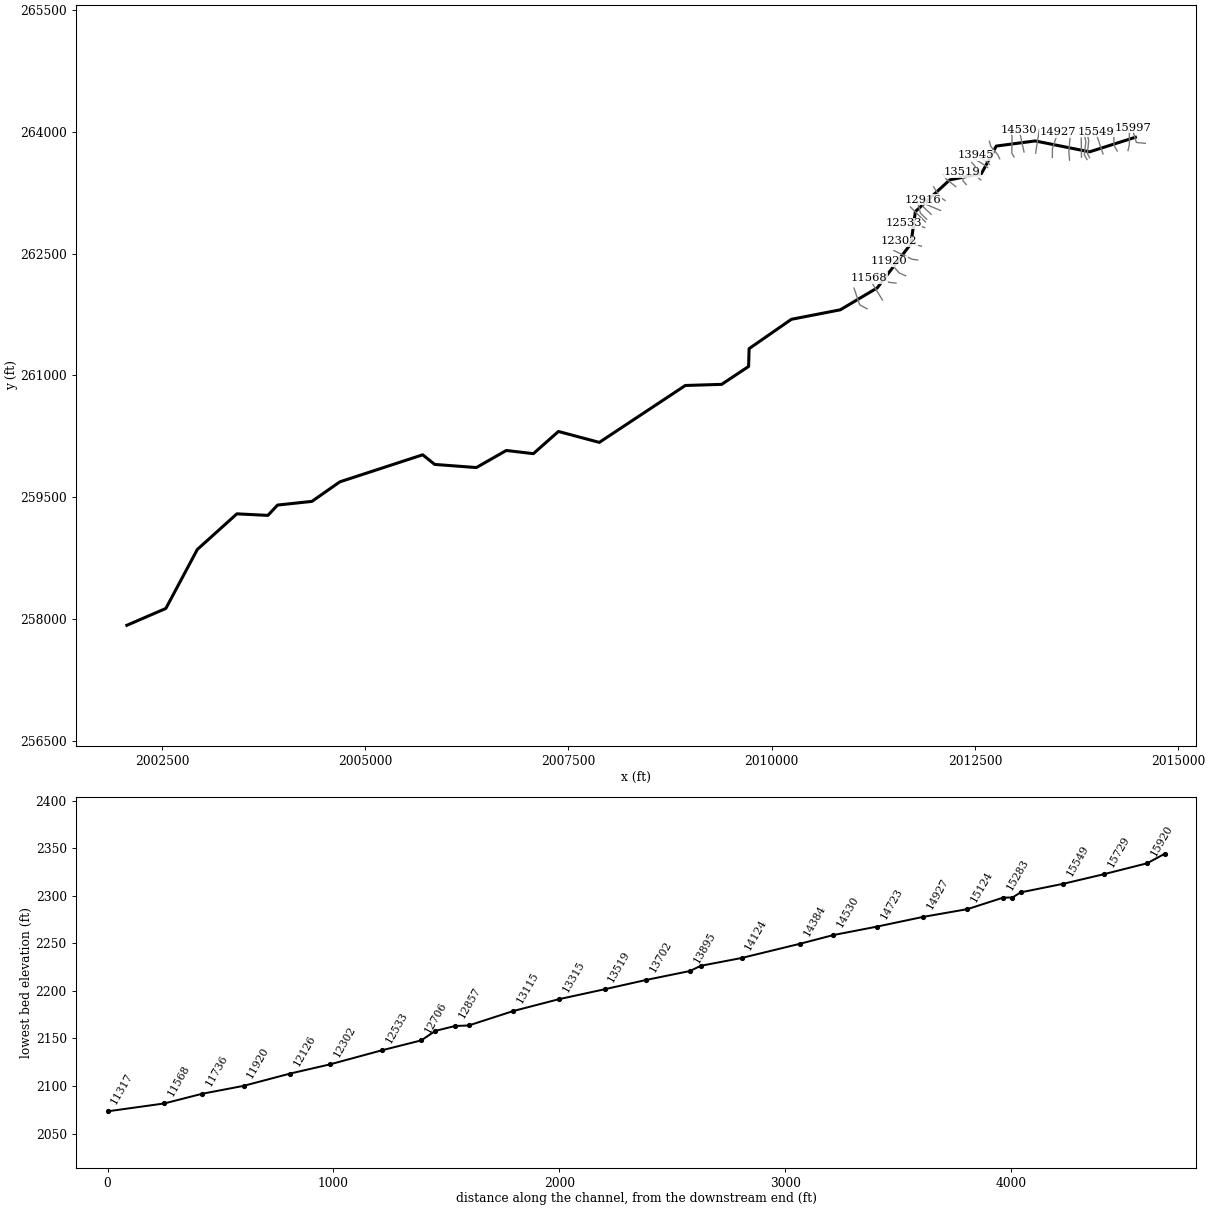
--- BRKSBR_A.prj (project) ---

Proj Title=BRKSBR_A
Current Plan=p01
Default Exp/Contr=0,0
English Units
Geom File=g01
Flow File=f01
Plan File=p01
BEGIN DESCRIPTION:
Stream Name: Brooks Branch
Flood Zone: Approximate
Summers County, West Virginia
HEC-RAS Version: 5.0.7
Hydrology Method:
regression
Model Notes:
KWSEL tie in to BRKSBR_AE
END DESCRIPTION:
DSS File=dss
DSS Export Rating Curves= 0
DSS Export Rating Curve Sorted= 0
DSS Export Volume Flow Curves= 0
DXF OffsetX= 0
DXF OffsetY= 0
DXF ScaleX= 0
DXF ScaleY= 0

--- BRKSBR_A.p01 (plan) ---

Plan Title=Floodplain
Program Version=5.07
Short Identifier=Floodplain
Geom File=g01
Flow File=f01
Subcritical Flow
K Sum by GR= 0
Std Step Tol= 0.01
Critical Tol= 0.01
Num of Std Step Trials= 20
Max Error Tol= 0.3
Flow Tol Ratio= 0.001
Split Flow NTrial= 30
Split Flow Tol= 0.02
Split Flow Ratio= 0.02
Log Output Level= 0
Friction Slope Method= 1
Unsteady Friction Slope Method= 2
Unsteady Bridges Friction Slope Method= 1
Parabolic Critical Depth
Global Vel Dist= 0 , 0 , 0
Global Log Level= 0
CheckData=True
Encroach Param=-1 ,0,0, 0
Computation Interval=0.1SEC
Output Interval=1MIN
Instantaneous Interval=Max Profile
Mapping Interval=1HOUR
Computation Time Step Use Courant=        0
Computation Time Step Use Time Series=    0
Computation Time Step Count To Double=0
Computation Time Step Max Doubling=0
Computation Time Step Max Halving=0
Computation Time Step Residence Courant=0
Run HTab= 0
Run UNet= 0
Run Sediment= 0
Run PostProcess= 0
Run WQNet= 0
Run RASMapper= 0
UNET Theta= 0
UNET Theta Warmup= 0
UNET ZTol= 0
UNET ZSATol= 0
UNET MxIter= 0
UNET Max Iter WO Improvement= 0
UNET MaxInSteps= 0
UNET DtIC= 0
UNET DtMin= 0
UNET MaxCRTS= 0
UNET WFStab= 0
UNET SFStab= 0
UNET WFX= 1
UNET SFX= 1
UNET 1D Methodology=Finite Difference
UNET DSS MLevel= 1
UNET Pardiso=0
UNET DZMax Abort= 0
UNET Use Existing IB Tables= 0
UNET Froude Reduction=False
UNET Froude Limit= 0
UNET Froude Power= 0
UNET D1 Cores= 0
UNET D2 Coriolis=0
UNET D2 Cores= 0
UNET D2 Theta= 1
UNET D2 Theta Warmup= 1
UNET D2 Z Tol= 0.01
UNET D2 Volume Tol= 0.01
UNET D2 Max Iterations= 20
UNET D2 Equation= 0
UNET D2 RampUpFraction=0.1
UNET D2 TimeSlices= 1
UNET D2 BCVolumeCheck=0
UNET D1D2 MaxIter= 0
UNET D1D2 ZTol=0.01
UNET D1D2 QTol=0.1
UNET D1D2 MinQTol=1
DSS File=dss
Write IC File= 0
Write IC File at Fixed DateTime=0
Write IC File at Sim End=0
Echo Input=False
Echo Parameters=False
Echo Output=False
Write Detailed= 0
HDF Write Warmup=0
HDF Write Time Slices=0
HDF Flush=0
HDF Face Node Velocities=0
HDF Compression= 1
HDF Chunk Size= 1
HDF Spatial Parts= 1
HDF Use Max Rows=0
HDF Fixed Rows= 1
Calibration Method= 0
Calibration Iterations= 20
Calibration Max Change=0.05
Calibration Tolerance=0.2
Calibration Maximum=1.5
Calibration Minimum=0.5
Calibration Optimization Method= 1
WQ AD Non Conservative
WQ ULTIMATE=-1
WQ Max Comp Step=1HOUR
WQ Output Interval=15MIN
WQ Output Selected Increments= 0
WQ Output face flow=0
WQ Output face velocity=0
WQ Output face area=0
WQ Output face dispersion=0
WQ Output cell volume=0
WQ Output cell surface area=0
WQ Output cell continuity=0
WQ Output cumulative cell continuity=0
WQ Output face conc=0
WQ Output face dconc_dx=0
WQ Output face courant=0
WQ Output face peclet=0
WQ Output face adv mass=0
WQ Output face disp mass=0
WQ Output cell mass=0
WQ Output cell source sink temp=0
WQ Output nsm pathways=0
WQ Output nsm derived pathways=0
WQ Output MaxMinRange=-1
WQ Daily Max Min Mean=-1
WQ Daily Range=0
WQ Daily Time=0
WQ Create Restart=0
WQ Fixed Restart=0
WQ System Summary=0
WQ Write To DSS=0
WQ Use Fixed Temperature=0
Sorting and Armoring Iterations= 10
XS Update Threshold= 0.02
Bed Roughness Predictor= 0
Hydraulics Update Threshold= 0.02
Energy Slope Method= 1
Volume Change Method= 1
Sediment Retention Method= 0
XS Weighting Method= 0
Number of US Weighted Cross Sections= 1
Number of DS Weighted Cross Sections= 1
Upstream XS Weight=0
Main XS Weight=1
Downstream XS Weight=0
Number of DS XS's Weighted with US Boundary= 1
Upstream Boundary Weight= 1
Weight of XSs Associated with US Boundary= 0
Number of US XS's Weighted with DS Boundary= 1
Downstream Boundary Weight= 0.5
Weight of XSs Associated with DS Boundary= 0.5
Percentile Method= 0
Sediment Output Level= 3
Mass or Volume Output= 0
Output Increment Type= 1
Profile and TS Output Increment= 1
XS Output Flag= 0
XS Output Increment= 10
Write Gradation File= 0
Read Gradation Hotstart= 0
Write HDF5 File= 1
Write Binary Output= 1
Write DSS Sediment File= 0
SV Curve= 0
Specific Gage Flag= 0

--- BRKSBR_A.f01 (steady flow) ---

Flow Title=Flows
Program Version=5.07
Number of Profiles= 6
Profile Names=01pct,10pct,04pct,02pct,0_2pct,01plus
River Rch & RM=BRKSBR_A,Main            ,15997
     564     298     396     478     788     835
River Rch & RM=BRKSBR_A,Main            ,13315
     630     334     444     534     879     932
River Rch & RM=BRKSBR_A,Main            ,11317
     705     376     498     598     981    1043
River Rch & RM=BRKSBR_A,Main            ,8875
     816     437     578     693    1133    1207
River Rch & RM=BRKSBR_A,Main            ,7307
     907     488     643     771    1256    1342
River Rch & RM=BRKSBR_A,Main            ,4354
    1010     545     718     859    1396    1494
River Rch & RM=BRKSBR_A,Main            ,0
    1034     559     735     880    1429    1529
Boundary for River Rch & Prof#=BRKSBR_A,Main            , 1
Up Type= 0
Dn Type= 1
Dn Known WS=1393.3
Boundary for River Rch & Prof#=BRKSBR_A,Main            , 2
Up Type= 0
Dn Type= 1
Dn Known WS=1392
Boundary for River Rch & Prof#=BRKSBR_A,Main            , 3
Up Type= 0
Dn Type= 1
Dn Known WS=1392.7
Boundary for River Rch & Prof#=BRKSBR_A,Main            , 4
Up Type= 0
Dn Type= 1
Dn Known WS=1393.1
Boundary for River Rch & Prof#=BRKSBR_A,Main            , 5
Up Type= 0
Dn Type= 1
Dn Known WS=1394.1
Boundary for River Rch & Prof#=BRKSBR_A,Main            , 6
Up Type= 0
Dn Type= 1
Dn Known WS=1394.3
DSS Import GetInterval= 0
DSS Import GetPeak= 0
DSS Import FillOption= 0

--- BRKSBR_A.g01 (geometry) ---

Geom Title=Geometry
Program Version=5.07

River Reach=BRKSBR_A        ,Main
Reach XY= 30
2014473.24899281263934.736644699     2013910.161       263755.67
     2013240.089      263889.722     2012762.311      263826.528
     2012580.104       263487.87     2012190.089      263409.861
2011767.36326559263019.416060161     2011712.311      262622.361
     2011297.944      262078.572     2010843.561      261808.472
2010241.74114644261691.419638664     2009722.034         261330.
2009715.65502861261110.4598672052009384.45584033260889.744027616
2008937.11981952      260875.833     2007878.978      260174.444
       2007376.2      260309.166     2007067.867      260035.555
     2006735.069      260074.997  2006366.680203259864.373680855
     2005853.978      259902.917     2005706.756      260021.667
     2004688.232      259688.6572004343.56241526259447.455591678
     2003920.793      259402.051     2003802.345      259274.806
     2003420.729      259293.945     2002934.036      258854.867
     2002547.034      258127.9172002067.10077195  257920.1478018

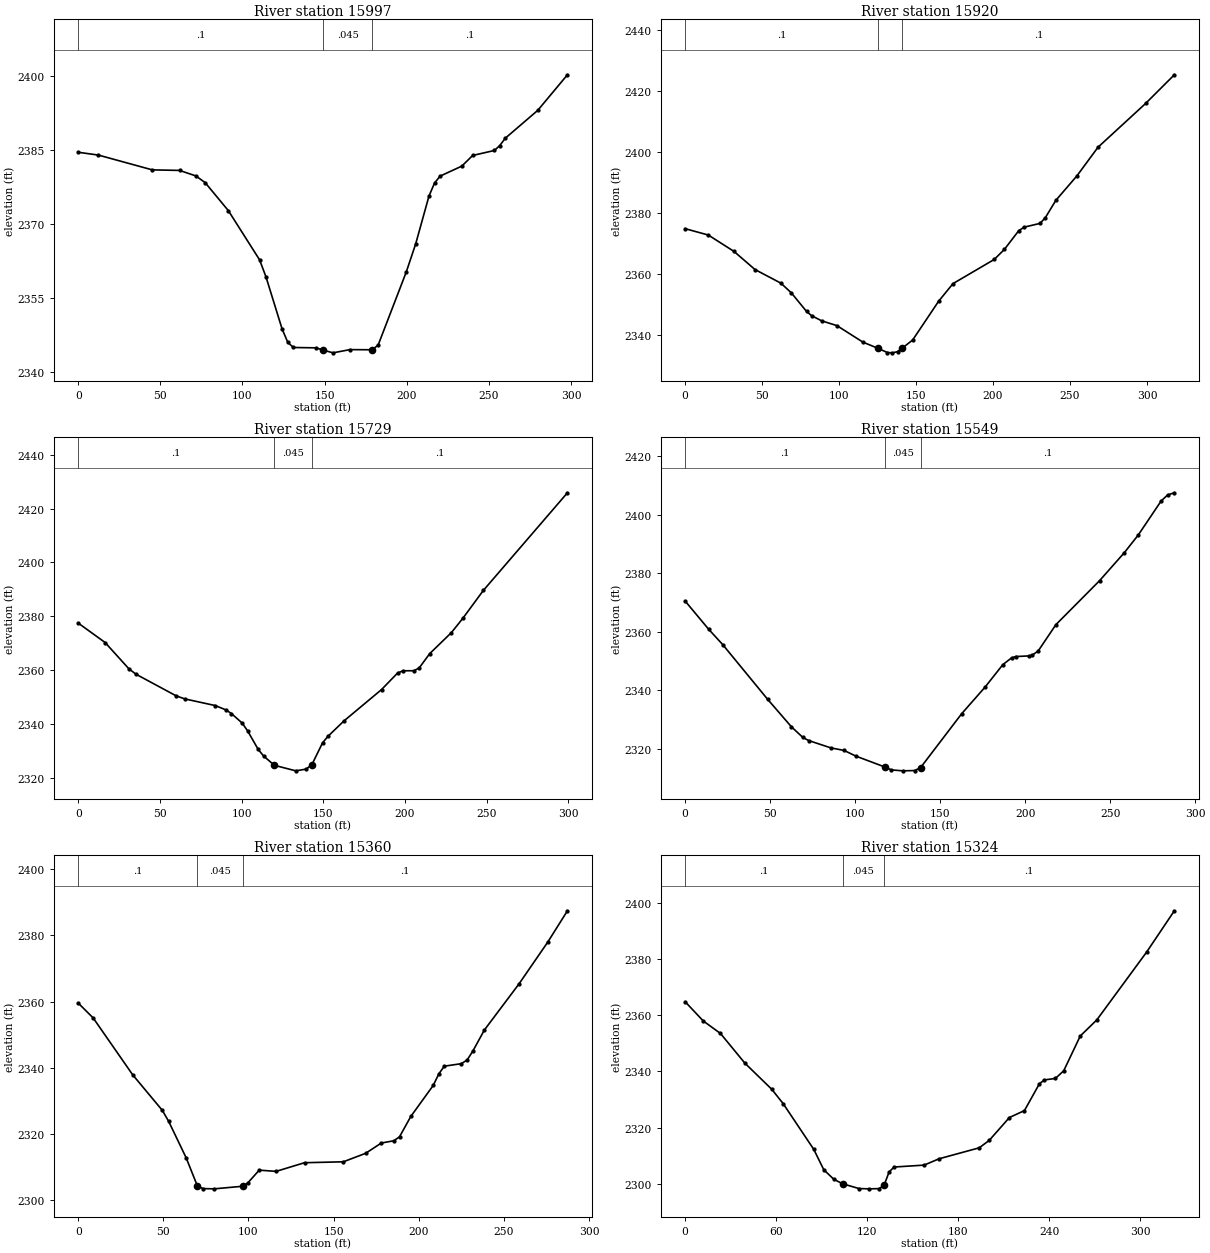
Type RM Length L Ch R = 1 ,15997   ,77,77,77
XS GIS Cut Line= 4
 2014595.7052413263860.1501496092014485.82405106263871.118138948
2014453.55900325263974.8486948972014445.35597563264053.133974694
#Sta/Elev= 30
       0 2384.51    12.3 2383.94    45.1 2380.95    61.7 2380.84    71.6 2379.73
    77.3 2378.37    91.4 2372.71   110.4 2362.77   114.3 2359.33   124.1 2348.81
   127.6 2346.07     131 2345.05   144.8 2344.98   149.2 2344.52   155.1 2343.97
   165.4 2344.62   179.1 2344.59   182.6 2345.56   199.7 2360.32   205.4 2365.96
   213.5 2375.64   216.9 2378.29   220.3 2379.69   233.5 2381.71   240.1 2383.86
   253.3 2384.87   256.6 2385.86   259.9 2387.33   279.7 2392.97   297.8 2400.17
#Mann= 3 ,-1 , 0
       0      .1       0   149.2    .045       0   179.1      .1       0
Bank Sta=149.2,179.1
XS Rating Curve= 0 ,0
Exp/Cntr(USF)=0,0
Exp/Cntr=0.3,0.1

Type RM Length L Ch R = 1 ,15920   ,191.4,190.8,190.7
XS GIS Cut Line= 4
2014382.88198613263771.114720406 2014399.2506307263841.770769046
 2014399.2506307263984.7375341032014369.37276116 264082.62090875
#Sta/Elev= 30
       0 2374.83    15.1 2372.73    31.8 2367.35    45.4 2361.42    62.2 2356.96
      69 2353.78    78.9 2347.67    82.2 2346.28    88.7  2344.6    98.6 2343.03
   115.5 2337.61   125.4 2335.56   131.4  2334.2   134.7  2334.1     138 2334.49
   141.2  2335.7   147.8  2338.3   164.7 2351.04     174  2356.8   200.8 2364.73
   207.4 2368.03   216.7 2374.15   220.2 2375.32   230.5 2376.55   233.9 2378.35
   240.8  2384.1   254.5 2392.14   268.2 2401.53   299.1 2415.88   317.8  2425.3
#Mann= 3 ,-1 , 0
       0      .1       0   125.4    .045       0   141.2      .1       0
Bank Sta=125.4,141.2
XS Rating Curve= 0 ,0
Exp/Cntr=0.3,0.1

Type RM Length L Ch R = 1 ,15729   ,173.9,180.1,184.2
XS GIS Cut Line= 3
 2014250.1249534263764.7473578282014209.42921154263838.767265578
2014208.82851085264053.818113858
#Sta/Elev= 30
       0 2377.51    16.5 2370.28    30.9 2360.62    35.3 2358.55    59.9 2350.52
    65.2 2349.37    83.9 2346.89    90.6 2345.24    93.8 2343.92   100.4 2340.38
   103.7  2337.5   110.2 2330.61   113.5 2328.16   120.1 2324.71   133.2 2322.66
   139.6 2323.31   143.1 2325.01   149.6 2333.07   152.9 2335.48   162.7 2341.19
   185.7 2352.83   195.5 2358.95   198.8  2359.8   205.4 2359.81   208.7 2360.82
   215.2 2366.17   228.4 2373.93   235.4 2379.22     248 2389.61   299.5 2425.87
#Mann= 3 ,-1 , 0
       0      .1       0   120.1    .045       0   143.1      .1       0
Bank Sta=120.1,143.1
XS Rating Curve= 0 ,0
Exp/Cntr=0.3,0.1

Type RM Length L Ch R = 1 ,15549   ,194.2,189.1,176.6
XS GIS Cut Line= 2
2014075.47295689263730.0404400512013983.56575078264002.758554909
#Sta/Elev= 30
       0  2370.5    13.8  2360.9    22.1 2355.64    48.5    2337    62.5 2327.61
    69.2 2323.98    72.7 2322.89    85.8 2320.38    93.5 2319.53   100.4  2317.6
   117.7 2313.82   121.2 2312.89   128.1 2312.56     135 2312.66   138.5 2313.65
   162.7 2332.05   176.5 2341.16   186.9 2348.79     192 2351.08   194.6 2351.56
   202.4 2351.77   204.3 2352.07   207.7 2353.45   218.1 2362.42   243.8 2377.43
   258.4 2387.01   266.6 2393.04     280  2404.6   283.9 2406.71   287.8 2407.42
#Mann= 3 ,-1 , 0
       0      .1       0   117.7    .045       0   138.5      .1       0
Bank Sta=117.7,138.5
XS Rating Curve= 0 ,0
Exp/Cntr=0.3,0.1

Type RM Length L Ch R = 1 ,15360   ,36.7,36.2,36
XS GIS Cut Line= 4
2013910.06460244263682.8203158362013883.78995411263733.909909821
2013899.36011608263896.4234754482013883.78995411263961.136961161
#Sta/Elev= 30
       0 2359.56     8.8 2355.06      32 2337.91    49.4 2327.18    53.1 2323.89
    63.4 2312.86      70 2304.36    73.3 2303.57    79.9  2303.5    96.8 2304.29
    99.7 2305.34   106.3 2309.14   116.2 2308.77   132.9 2311.38   155.7 2311.66
   168.8 2314.22     178 2317.32   185.4 2318.01   188.7 2319.21   195.3 2325.33
   208.5 2334.72   211.8 2338.21     215 2340.51     225 2341.27   228.4 2342.38
   231.8 2345.11   238.5 2351.41   258.8  2365.3   275.7 2377.92   287.3  2387.4
#Mann= 3 ,-1 , 0
       0      .1       0      70    .045       0    96.8      .1       0
Bank Sta=70,96.8
XS Rating Curve= 0 ,0
Exp/Cntr(USF)=0,0
Exp/Cntr=0.3,0.1

Type RM Length L Ch R = 1 ,15324   ,39.4,41.3,44.1
XS GIS Cut Line= 4
2013878.49959876263660.4463306642013845.36779745263720.129449883
2013864.52110945263884.1779335532013844.35335411263970.794203715
#Sta/Elev= 30
       0 2364.88      12 2357.99    23.3 2353.55    39.4 2342.95    57.1 2333.64
    64.6 2328.53    84.8 2312.19    91.4 2304.91      98 2301.53   103.8 2299.92
   114.6 2298.22   121.2 2298.12   127.8 2298.19   131.1 2299.33   134.4 2304.13
   137.7  2305.9   157.5 2306.58   167.4 2308.85   193.8 2312.75   200.4  2315.4
   213.7 2323.56   223.6 2326.03   233.5 2335.62   236.8 2336.98     244  2337.5
   249.5 2340.24   260.4 2352.65   271.3 2358.38   304.1 2382.56   322.4 2397.31
#Mann= 3 ,-1 , 0
       0      .1       0   103.8    .045       0   131.1      .1       0
Bank Sta=103.8,131.1
XS Rating Curve= 0 ,0
Exp/Cntr=0.3,0.1

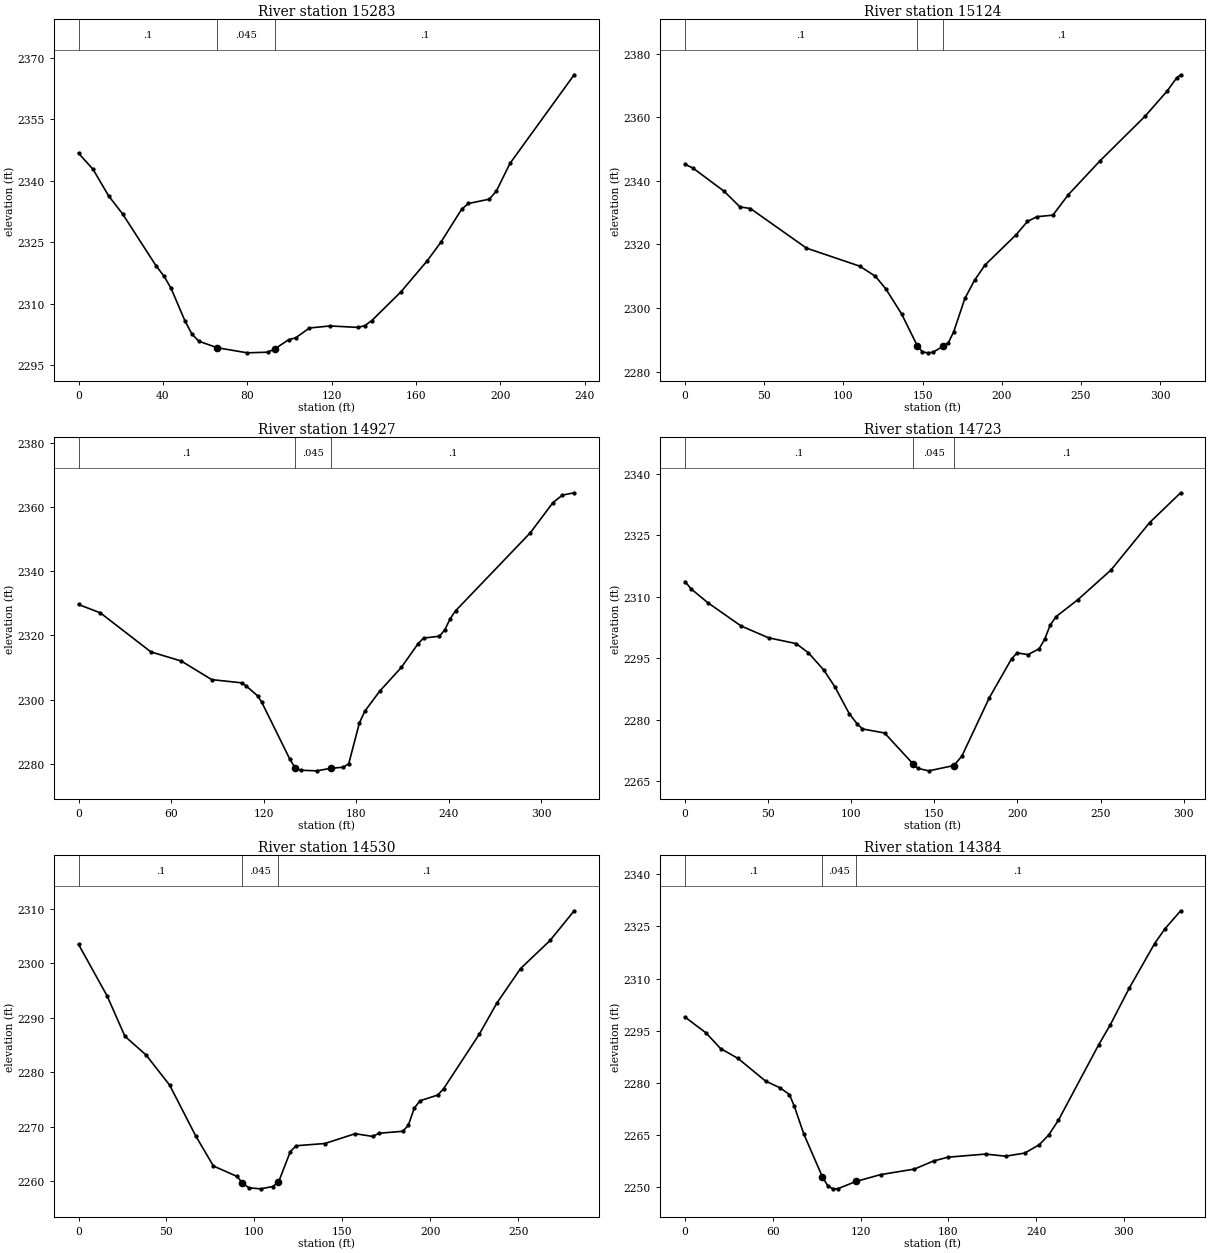
Type RM Length L Ch R = 1 ,15283   ,160.8,158.3,154.8
XS GIS Cut Line= 2
2013810.20637341263689.4479345332013807.75823743 263924.43945586
#Sta/Elev= 30
       0 2346.69     6.9 2342.74    14.3 2336.27    20.9 2331.88    36.7 2319.28
    40.6 2316.64    43.9 2313.71    50.4 2305.87    53.7 2302.64      57 2300.84
    65.82299.246      80    2298    89.8 2298.16    93.1 2298.97    99.6  2301.2
   102.9 2301.65   109.5 2304.06   119.3 2304.56   132.5  2304.2   135.7 2304.63
     139 2305.84   152.8 2312.83   165.3 2320.43   171.8 2324.97   181.7 2333.06
   184.9 2334.42   194.8 2335.48   198.1 2337.45   204.6 2344.22     235 2365.81
#Mann= 3 ,-1 , 0
       0      .1       0    65.8    .045       0    93.1      .1       0
Bank Sta=65.8,93.1
XS Rating Curve= 0 ,0
Exp/Cntr(USF)=0,0
Exp/Cntr=0.3,0.1

Type RM Length L Ch R = 1 ,15124   ,199.9,196.9,191.9
XS GIS Cut Line= 3
2013663.56289492263652.8099121752013655.25402707263759.049514072
2013672.38082159 263964.63187036
#Sta/Elev= 30
       0 2345.27     5.1 2344.03    24.8 2336.71    34.7 2331.83    41.3 2331.32
    76.7 2318.85   110.4 2313.15   120.2 2309.98   126.8    2306   136.7 2298.17
   146.6 2288.18   149.9 2286.17   153.2 2285.88   156.5 2286.05     163 2287.95
   166.3 2289.11   169.6 2292.46   176.7 2303.01   182.8 2308.73   189.4 2313.53
   209.1 2323.08   216.2 2327.26   222.3 2328.75   232.2 2329.22   242.1 2335.72
   261.8 2346.22   290.5  2360.4   304.4 2368.31   310.4 2372.46   312.9 2373.42
#Mann= 3 ,-1 , 0
       0      .1       0   146.6    .045       0     163      .1       0
Bank Sta=146.6,163
XS Rating Curve= 0 ,0
Exp/Cntr=0.3,0.1

Type RM Length L Ch R = 1 ,14927   ,202,204.5,207.7
XS GIS Cut Line= 3
2013452.39492068263686.4038799832013452.74772295 263794.90694647
2013520.82166521263996.457139332
#Sta/Elev= 30
       0 2329.69    14.1 2327.08    46.9 2314.88    66.6 2312.02    86.3 2306.21
     106 2305.19   108.5 2304.29     116 2301.17   118.6 2299.29     137  2281.3
   140.4 2278.63   143.9  2277.9   154.3 2277.71   163.8 2278.52   171.6 2278.84
   175.1 2279.91     182 2292.64   185.5 2296.32   195.1 2302.56   209.2 2310.03
   220.1 2317.47   223.6 2319.19   233.9 2319.77   237.4  2321.8   240.9 2325.29
   244.3 2327.69   292.8  2352.1   307.5 2361.55   313.6 2363.86   321.2 2364.59
#Mann= 3 ,-1 , 0
       0      .1       0   140.4    .045       0   163.8      .1       0
Bank Sta=140.4,163.8
XS Rating Curve= 0 ,0
Exp/Cntr=0.3,0.1

Type RM Length L Ch R = 1 ,14723   ,187.1,192.7,199.8
XS GIS Cut Line= 2
2013245.89081329263739.376866859 2013292.4956974264033.945023442
#Sta/Elev= 30
       0 2313.71     3.8 2311.87    13.8 2308.53    33.7 2302.87    50.3 2299.97
    66.9 2298.55    74.2 2296.33    83.5 2292.11    90.2 2287.98    98.8 2281.47
   103.5 2278.99   106.8 2277.71   120.1 2276.72   137.3 2269.13     140 2268.09
   146.7 2267.48   161.8 2268.78   166.6 2271.08   183.1 2285.33   196.5 2294.85
   199.8 2296.28   206.4 2295.87   213.1 2297.31   216.4 2299.63   219.7 2303.04
   223.3 2305.16   236.3 2309.26   256.3 2316.53   279.5 2328.09   298.2 2335.39
#Mann= 3 ,-1 , 0
       0      .1       0   137.3    .045       0   161.8      .1       0
Bank Sta=137.3,161.8
XS Rating Curve= 0 ,0
Exp/Cntr=0.3,0.1

Type RM Length L Ch R = 1 ,14530   ,149.5,146.7,141
XS GIS Cut Line= 2
2013103.54458394263753.4536966032013043.98871438 264028.89959331
#Sta/Elev= 30
       0 2303.49    16.3    2294    26.4 2286.61    38.4 2283.19    51.8 2277.66
    66.7 2268.29    76.7 2262.81    90.2 2260.89    93.2 2259.68    96.9  2258.8
   103.6 2258.62   110.3 2259.04   113.7 2259.84   120.4 2265.44   123.7 2266.53
   140.1 2266.94   157.3 2268.74   167.4 2268.23   170.7 2268.82   184.3 2269.18
   187.5 2270.27   190.9 2273.45   194.2 2274.79   204.3 2275.84   207.6 2277.01
   227.8 2286.97   237.9 2292.74   251.3 2299.04   268.1  2304.2   281.8 2309.65
#Mann= 3 ,-1 , 0
       0      .1       0    93.2    .045       0   113.7      .1       0
Bank Sta=93.2,113.7
XS Rating Curve= 0 ,0
Exp/Cntr=0.3,0.1

Type RM Length L Ch R = 1 ,14384   ,248.2,259.3,268.9
XS GIS Cut Line= 4
2012981.20362148263692.6442032162012952.58167687263741.236602202
2012956.89806587263946.9844809772012930.85639924264019.033092082
#Sta/Elev= 30
       0 2298.94    14.4 2294.37    24.3 2289.89    36.3 2287.02    55.1 2280.51
    64.9  2278.6    71.4 2276.65    74.7 2273.32    81.3 2265.22      94 2252.91
    97.7 2250.34     101 2249.56   104.3 2249.53   116.82251.643   133.8 2253.63
   156.8 2255.21   169.9 2257.54   179.7 2258.63   205.5 2259.53   219.1 2258.92
   232.2 2259.81   242.1 2262.19   248.6 2265.01   255.2 2269.22   282.7 2290.91
   290.6 2296.61   303.6 2307.19     321 2320.06     328 2324.28   338.8  2329.5
#Mann= 3 ,-1 , 0
       0      .1       0      94    .045       0   116.8      .1       0
Bank Sta=94,116.8
XS Rating Curve= 0 ,0
Exp/Cntr(USF)=0,0
Exp/Cntr=0.3,0.1

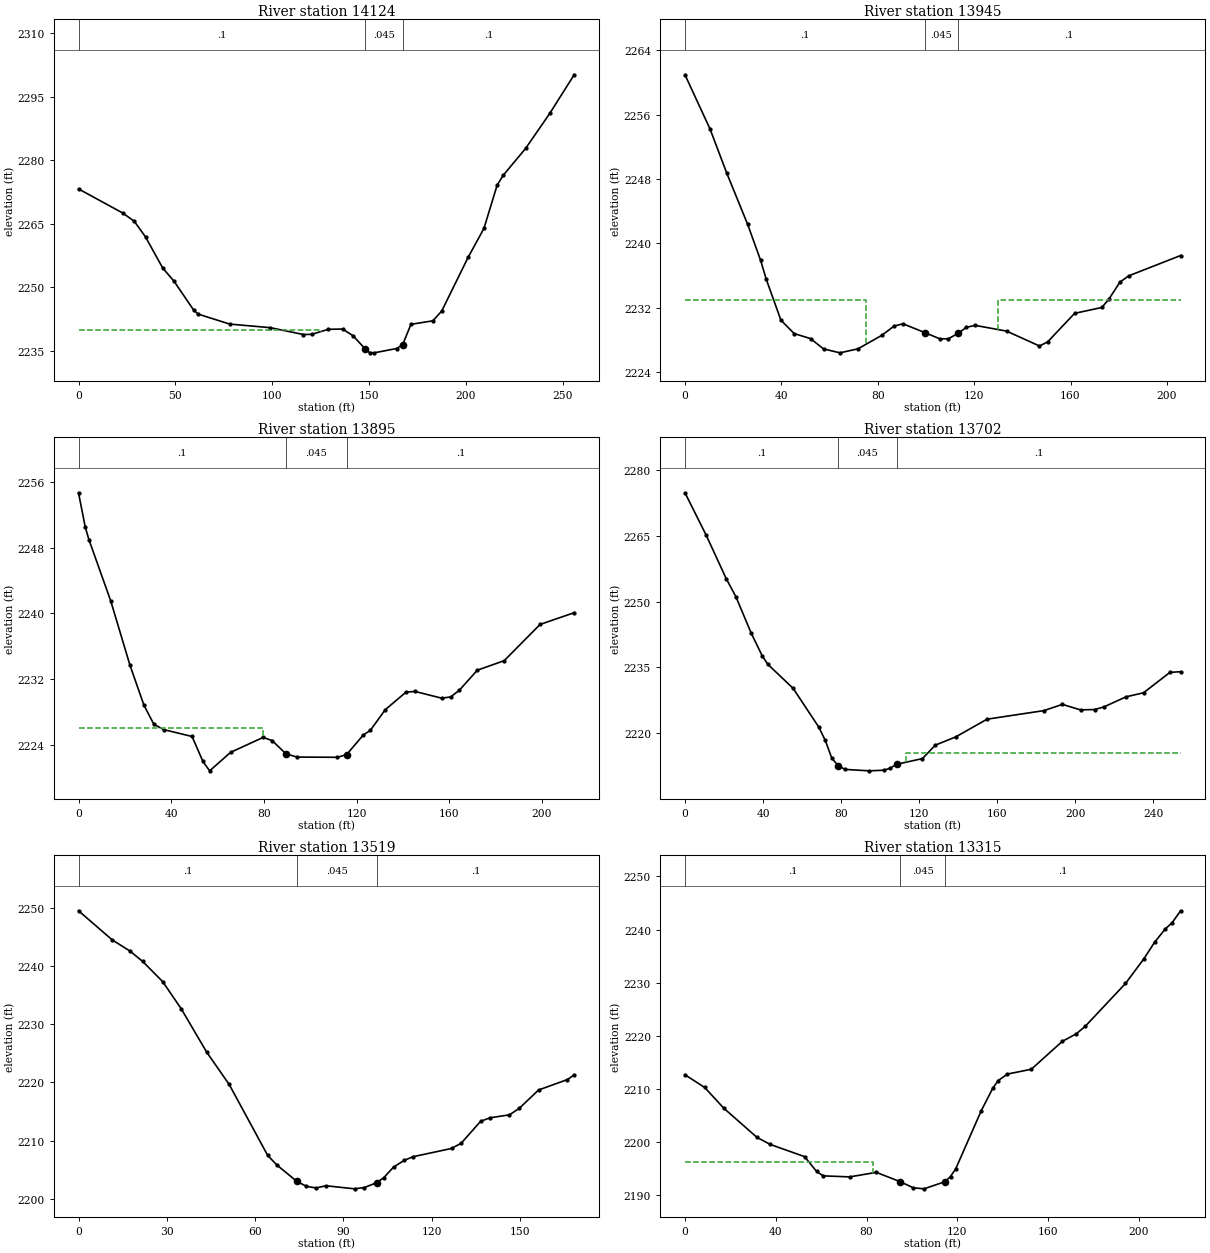
Type RM Length L Ch R = 1 ,14124   ,175.6,179.8,185.2
XS GIS Cut Line= 4
 2012804.9444428263669.4880424862012779.45588842263720.940609024
2012694.77228579263822.7292667692012677.26747312263886.513437685
#Sta/Elev= 30
       0 2273.23    22.9 2267.52    28.8 2265.59    34.6  2261.9    43.5 2254.54
    49.3 2251.46    59.5  2244.6    61.8 2243.67    78.1 2241.32    99.1 2240.47
   116.2 2238.85   120.5  2238.9     129 2240.08   136.4 2240.15   141.8 2238.56
     148 2235.49   150.3  2234.6   152.7 2234.53   164.3 2235.55   167.4 2236.45
   171.7 2241.26     183 2242.09   187.6  2244.4   201.2 2257.05   209.4  2263.9
   216.2 2274.09   219.3 2276.41   230.9 2282.77   243.4 2291.05     256 2300.17
#Mann= 3 ,-1 , 0
       0      .1       0     148    .045       0   167.4      .1       0
#XS Ineff= 2 , 0
             125    2240
Permanent Ineff=
       F       F
Bank Sta=148,167.4
XS Rating Curve= 0 ,0
Exp/Cntr=0.3,0.1

Type RM Length L Ch R = 1 ,13945   ,50.9,49.5,48.6
XS GIS Cut Line= 3
2012677.12729311263600.4739258472012651.11539126263633.185863025
2012507.65581135263712.403927758
#Sta/Elev= 30
       0 2260.94    10.4  2254.2    17.3 2248.74      26 2242.35    31.4 2237.86
    33.7 2235.54    39.8 2230.44    45.3 2228.77    52.1 2228.14    57.5 2226.86
    64.3 2226.37    71.8 2226.87    81.7 2228.55    86.8  2229.7    90.5 2229.98
    99.52228.891   105.8 2228.11   109.3 2228.12   113.32228.778   116.8 2229.55
   120.5 2229.78   133.5 2229.07   147.1 2227.22   150.5 2227.73   161.7 2231.28
     173 2232.01   175.9 2233.03   180.5 2235.16   184.2 2235.95   205.7 2238.47
#Mann= 3 ,-1 , 0
       0      .1       0    99.5    .045       0   113.3      .1       0
#XS Ineff= 2 , 0
              75    2233     130            2233
Permanent Ineff=
       F       F
Bank Sta=99.5,113.3
XS Rating Curve= 0 ,0
Exp/Cntr(USF)=0,0
Exp/Cntr=0.3,0.1

Type RM Length L Ch R = 1 ,13895   ,208.7,193.4,170.7
XS GIS Cut Line= 3
2012656.63306741263561.8501927942012621.55641188263590.226812997
2012477.70271225263678.509631405
#Sta/Elev= 30
       0 2254.71     2.9 2250.54     4.5 2248.99    13.9 2241.53    22.2 2233.69
    28.2 2228.84    32.5 2226.49    36.7 2225.84      49    2225    53.7 2221.95
    56.6 2220.81    65.6 2223.06    79.7 2224.89    83.6 2224.49    89.5 2222.89
    94.3 2222.49   111.7 2222.46   115.7 2222.79   122.9 2225.18   125.9 2225.73
   132.4 2228.27   141.3  2230.4   145.2 2230.49   156.7 2229.67   160.6 2229.82
   164.4 2230.65   172.1 2233.08   183.7 2234.24   199.2 2238.66   213.9 2240.09
#Mann= 3 ,-1 , 0
       0      .1       0    89.5    .045       0   115.7      .1       0
#XS Ineff= 2 , 0
           79.44    2226
Permanent Ineff=
       F       F
Bank Sta=89.5,115.7
XS Rating Curve= 0 ,0
Exp/Cntr(USF)=0,0
Exp/Cntr=0.3,0.1

Type RM Length L Ch R = 1 ,13702   ,185.3,183,182.8
XS GIS Cut Line= 4
2012572.08914369263408.1438269442012531.52228605263442.262532167
2012514.68420259263559.8822932282012461.70977843263622.702362239
#Sta/Elev= 30
       0 2274.81    10.8 2265.21    21.1 2255.27    26.1 2251.13    33.9 2242.86
    39.6 2237.63    42.5  2235.7    55.4 2230.26    68.6  2221.4    71.9 2218.38
    75.3 2214.27    78.6 2212.63    81.9 2211.78    94.4 2211.45   101.8 2211.59
   105.1 2212.03   108.4 2212.94   121.7 2214.24   128.3 2217.31   138.7 2219.17
   154.8 2223.22   183.9 2225.17   193.4 2226.59   202.7 2225.34   209.9 2225.42
   214.7 2226.02     226 2228.31     235 2229.24   248.5 2233.88     254 2234.04
#Mann= 3 ,-1 , 0
       0      .1       0    78.6    .045       0   108.4      .1       0
#XS Ineff= 2 , 0
                          113.24         2215.45
Permanent Ineff=
       F       F
Bank Sta=78.6,108.4
XS Rating Curve= 0 ,0
Exp/Cntr=0.3,0.1

Type RM Length L Ch R = 1 ,13519   ,179.5,203.2,208
XS GIS Cut Line= 3
2012392.95013469263352.8107576822012352.75757552263398.385610387
2012345.94562966263505.917041534
#Sta/Elev= 30
       0  2249.5    11.5 2244.48    17.4 2242.61    21.8  2240.8    28.6 2237.33
    34.9 2232.67    43.6 2225.18    51.2 2219.67    64.3 2207.46    67.4 2205.82
    74.2    2203    77.5 2202.14    80.8 2201.86    84.1 2202.24    93.9 2201.71
    97.2 2201.94   101.4 2202.77   103.8 2203.64   107.1 2205.45   110.7  2206.6
   113.8 2207.24   126.8 2208.65   130.1 2209.55   136.7 2213.32   139.9 2213.92
   146.5 2214.43   149.8 2215.53   156.4  2218.7   166.2 2220.49   168.5 2221.29
#Mann= 3 ,-1 , 0
       0      .1       0    74.2    .045       0   101.4      .1       0
Bank Sta=74.2,101.4
XS Rating Curve= 0 ,0
Exp/Cntr=0.3,0.1

Type RM Length L Ch R = 1 ,13315   ,206.1,200.9,197.6
XS GIS Cut Line= 3
2012264.20227928263326.3736112482012143.04695641263423.200556036
2012110.32118625 263477.35508314
#Sta/Elev= 30
       0 2212.68     8.7 2210.29    17.1 2206.39    31.7 2200.91    37.6 2199.57
    52.7 2197.28      58 2194.49    60.9 2193.66    72.6 2193.47    84.3 2194.32
    94.8 2192.57   100.6 2191.42   105.3 2191.22   114.6 2192.57     117 2193.54
   119.3 2194.99   130.5 2205.88   135.6 2210.13     138  2211.6   142.1 2212.82
   152.6 2213.72   166.2 2218.95   172.4 2220.39   176.3 2221.77   194.1 2229.86
   202.1 2234.44   206.9  2237.6   211.6 2240.11   214.6 2241.27   218.4 2243.54
#Mann= 3 ,-1 , 0
       0      .1       0    94.8    .045       0   114.6      .1       0
#XS Ineff= 2 , 0
           82.68 2196.33
Permanent Ineff=
       F       F
Bank Sta=94.8,114.6
XS Rating Curve= 0 ,0
Exp/Cntr=0.3,0.1

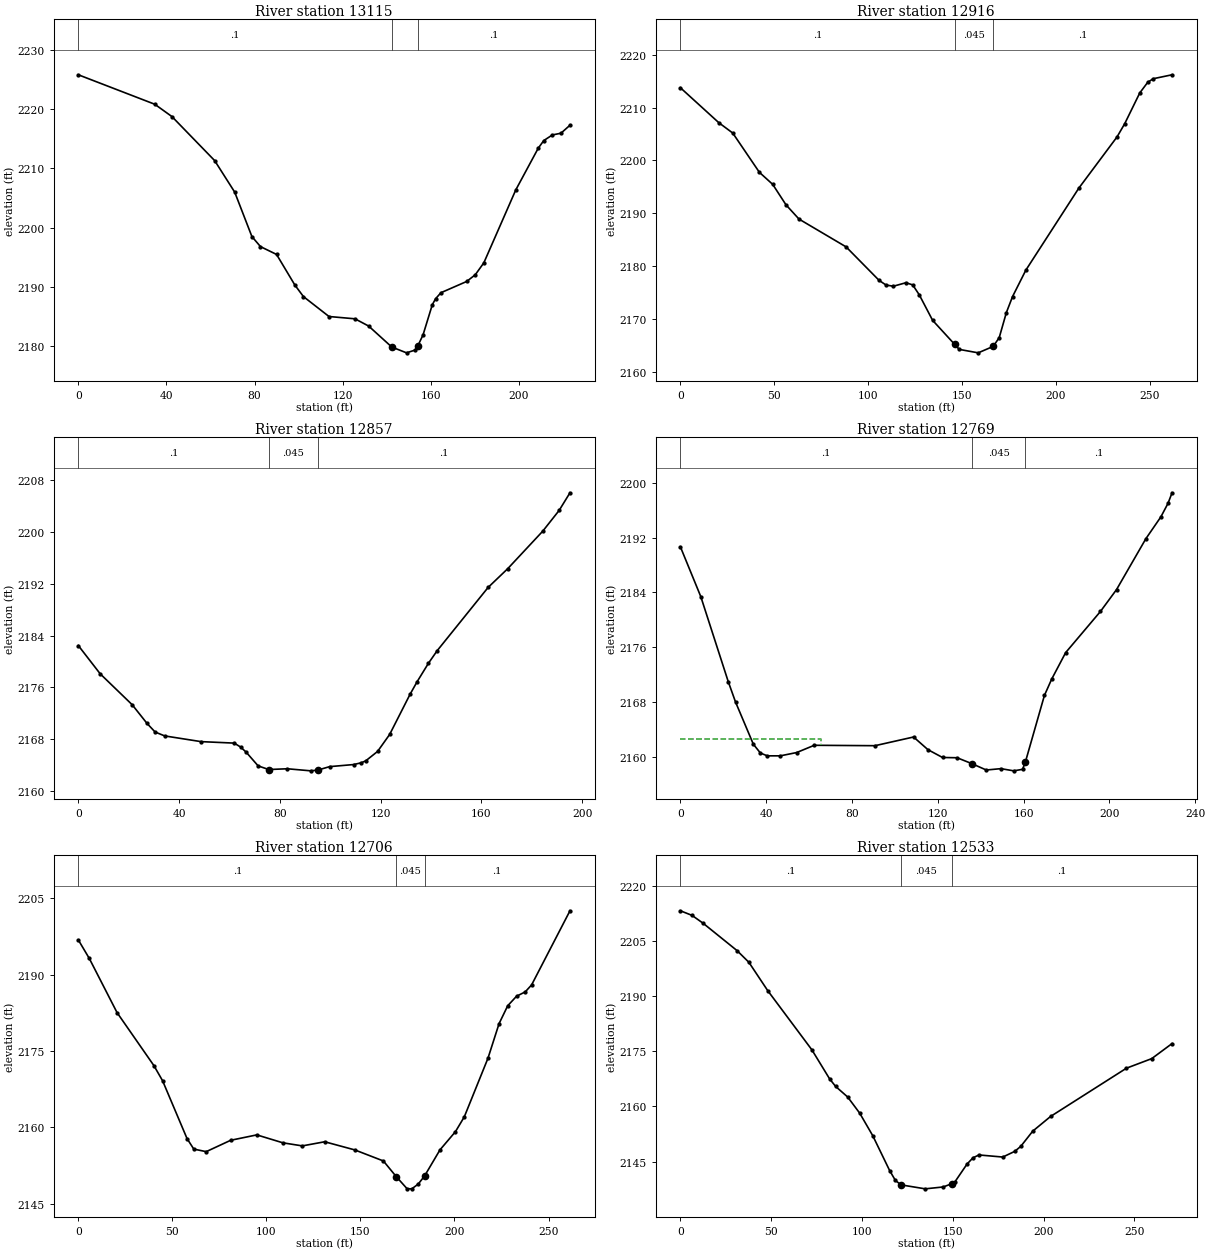
Type RM Length L Ch R = 1 ,13115   ,190,198.3,204.3
XS GIS Cut Line= 3
2012132.54820782263156.1246463982012075.70825895263192.076360302
2011991.49040355263323.371798102
#Sta/Elev= 30
       0 2225.77    34.7  2220.8    42.5 2218.72    61.9 2211.29      71 2205.97
    78.8 2198.48    82.7 2196.78      90 2195.46    98.3  2190.3   102.2 2188.35
   113.8 2184.99   125.6  2184.6   131.8 2183.38   142.3 2179.84     149 2178.86
   152.9 2179.33   154.1 2180.02   156.5 2181.89   160.7 2186.98   162.2 2187.99
   164.6    2189   176.3  2190.9   180.2 2192.03   184.1 2194.05   198.6 2206.35
   208.8 2213.39   211.3 2214.67   215.2 2215.62   219.1 2215.91   223.2 2217.26
#Mann= 3 ,-1 , 0
       0      .1       0   142.3    .045       0   154.1      .1       0
Bank Sta=142.3,154.1
XS Rating Curve= 0 ,0
Exp/Cntr=0.3,0.1

Type RM Length L Ch R = 1 ,12916   ,65.2,59.4,54
XS GIS Cut Line= 3
2012076.49568641263033.4724526722011905.99417328263103.956037723
2011860.04633245263166.342267933
#Sta/Elev= 30
       0 2213.74    20.5 2207.12    27.9 2205.17    42.1 2197.74    49.2 2195.46
    56.3 2191.58    63.2  2188.9    88.3 2183.64   105.9  2177.3   109.6 2176.42
   113.5  2176.2   120.2 2176.86   123.8 2176.45   127.3 2174.57   134.4 2169.75
   146.1 2165.22   148.6 2164.25   158.7  2163.6   166.7 2164.82   169.9 2166.48
   173.7 2171.21     177 2174.24   184.1 2179.25   212.3 2194.74   232.7 2204.45
   236.8 2206.96   244.8 2212.76     249 2214.75   251.9 2215.44     262 2216.19
#Mann= 3 ,-1 , 0
       0      .1       0   146.1    .045       0   166.7      .1       0
Bank Sta=146.1,166.7
XS Rating Curve= 0 ,0
Exp/Cntr=0.3,0.1

Type RM Length L Ch R = 1 ,12857   ,91.9,87.9,78.1
XS GIS Cut Line= 3
2011961.18832118262985.1162757542011867.78194635263074.581453334
2011845.31712202263136.458250163
#Sta/Elev= 30
       0 2182.45     8.7 2178.08    21.4 2173.31    27.3 2170.42    30.5  2169.1
    34.3  2168.5    48.7 2167.62    61.9 2167.39    64.4 2166.79    66.6 2166.01
    71.4 2163.87    75.62163.313      83 2163.43    92.3 2163.11    95.1 2163.23
    99.8 2163.76   109.3 2164.08   112.3 2164.35   114.1 2164.65   118.8  2166.1
   123.6 2168.72   131.7 2174.92   134.5 2176.86     139 2179.71   142.5 2181.67
   162.7 2191.42   170.5 2194.32   184.4 2200.11   190.9 2203.31   195.2 2206.03
#Mann= 3 ,-1 , 0
       0      .1       0    75.6    .045       0    95.1      .1       0
Bank Sta=75.6,95.1
XS Rating Curve= 0 ,0
Exp/Cntr(USF)=0,0
Exp/Cntr=0.3,0.1

Type RM Length L Ch R = 1 ,12769   ,52.1,62.8,68.2
XS GIS Cut Line= 3
2011906.01155967262925.6041972752011829.55233302262999.304585855
2011798.41687474263118.328742812
#Sta/Elev= 30
       0 2190.65     9.5 2183.39    22.3 2170.98    25.7    2168      34 2161.84
    37.3 2160.55    40.5 2160.14    46.6 2160.14    54.2 2160.62    62.4 2161.68
    90.7 2161.62   108.7 2162.89   115.4 2161.04   122.2  2159.9     129 2159.86
   135.8 2159.01   142.6 2158.07   149.4 2158.27   155.4 2157.95   159.5 2158.17
   160.8 2159.21   169.7 2168.96   173.1 2171.35   179.6 2175.21   195.8 2181.21
   203.3  2184.4     217 2191.84     224 2195.03   227.3 2196.99   229.2 2198.54
#Mann= 3 ,-1 , 0
       0      .1       0   135.8    .045       0   160.8      .1       0
#XS Ineff= 2 , 0
           65.63 2162.63
Permanent Ineff=
       F       F
Bank Sta=135.8,160.8
XS Rating Curve= 0 ,0
Exp/Cntr(USF)=0,0
Exp/Cntr=0.3,0.1

Type RM Length L Ch R = 1 ,12706   ,163.4,173.3,181.3
XS GIS Cut Line= 2
2011890.75023021262891.2630495352011705.80606487 263075.97375674
#Sta/Elev= 30
       0 2196.79     5.8 2193.18    20.6 2182.52    40.2 2172.11    44.8 2169.15
    57.8  2157.8    61.4 2155.73      68 2155.23      81 2157.46    94.9 2158.52
   108.8 2156.96   119.1 2156.36     131 2157.17     147 2155.57   162.2  2153.4
   169.1  2150.3   174.8 2147.95   177.3 2147.93   180.7 2148.86   184.1 2150.46
   192.3 2155.59   200.5 2159.15   205.2 2162.05   217.8 2173.57   223.7 2180.36
   228.3 2183.87     233 2185.74   237.6 2186.59     241 2187.96   261.4 2202.51
#Mann= 3 ,-1 , 0
       0      .1       0   169.1    .045       0   184.1      .1       0
Bank Sta=169.1,184.1
XS Rating Curve= 0 ,0
Exp/Cntr=0.3,0.1

Type RM Length L Ch R = 1 ,12533   ,233.7,231,227.8
XS GIS Cut Line= 4
 2011882.8187139262821.1621524782011815.64979923262844.834572889
2011683.44244022262852.3757131572011620.16291557262874.704643222
#Sta/Elev= 30
       0 2213.25     6.4    2212    12.5 2209.86    31.2 2202.41    37.7 2199.24
    48.1 2191.51    72.4 2175.41    82.2 2167.48    85.5 2165.44    92.1 2162.58
    98.7  2158.2   105.9 2152.06   115.2 2142.57   118.4 2139.86   121.5 2138.67
   134.8 2137.59   144.7  2138.1   149.4 2138.98   151.2 2139.53   157.8 2144.32
   161.1 2146.04   164.4 2146.81   177.5 2146.24   184.1 2147.79   187.4 2149.15
     194 2153.29   203.8 2157.28   245.6 2170.42   259.5 2173.02   270.7 2177.12
#Mann= 3 ,-1 , 0
       0      .1       0   121.5    .045       0   149.4      .1       0
Bank Sta=121.5,149.4
XS Rating Curve= 0 ,0
Exp/Cntr=0.3,0.1

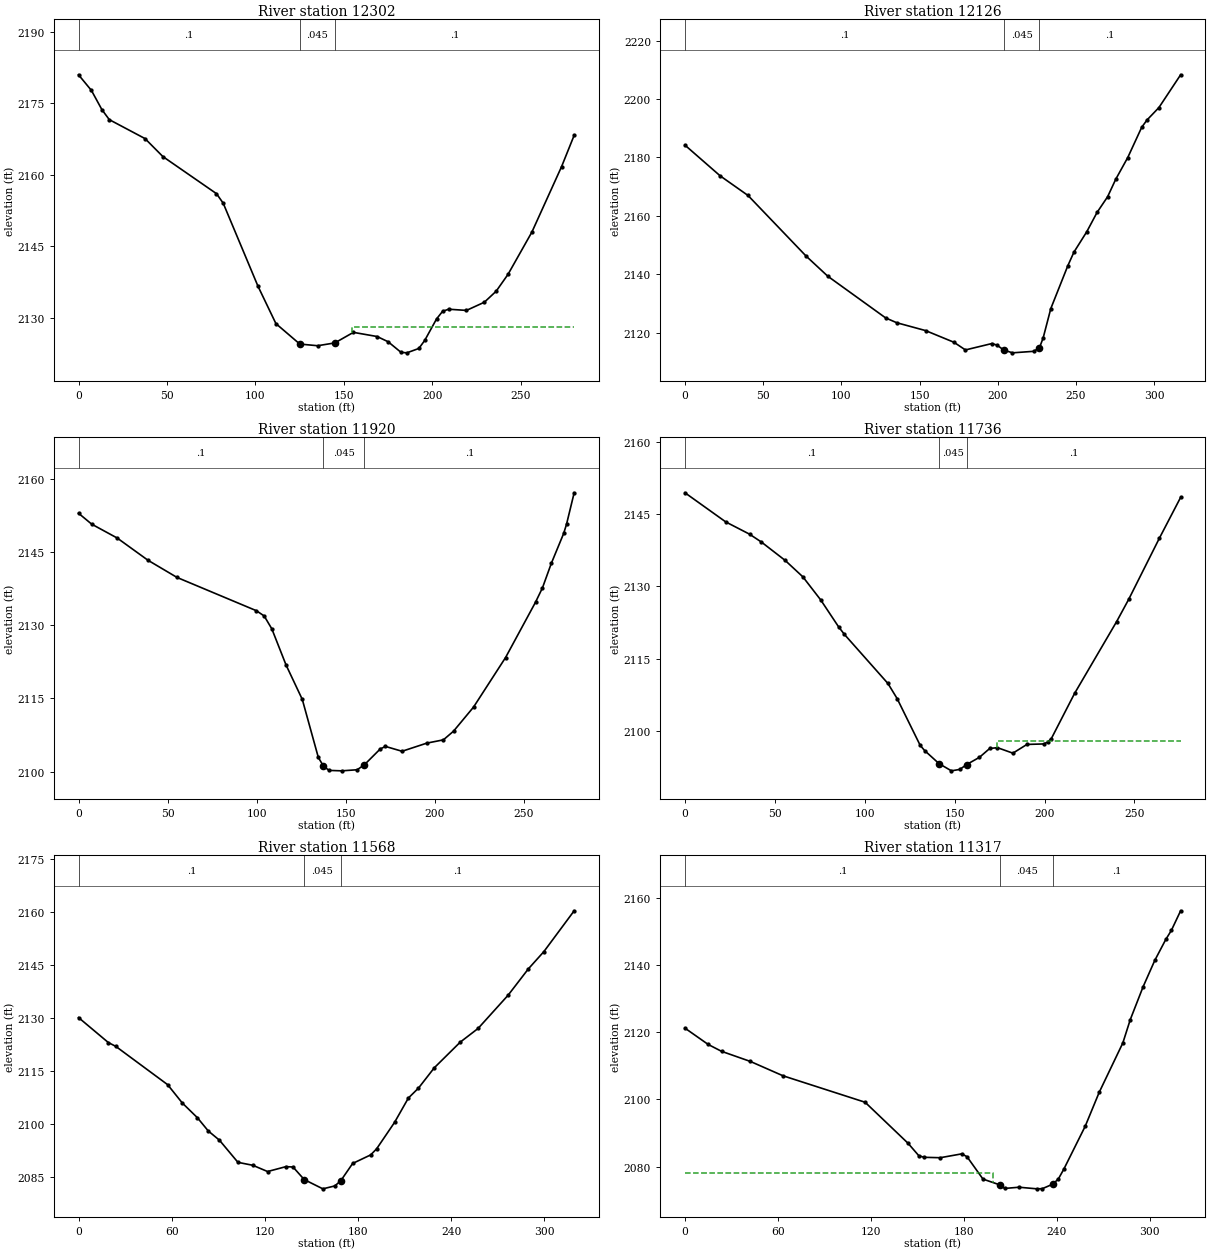
Type RM Length L Ch R = 1 ,12302   ,176.7,175.3,170.9
XS GIS Cut Line= 2
2011841.33421471262592.7883147592011568.01539915262654.660486191
#Sta/Elev= 30
       0 2180.97     7.3 2177.69    13.2 2173.68    17.4 2171.57    37.6  2167.6
    47.7 2163.83      78 2156.06    81.8 2154.06   101.5 2136.63   111.6 2128.83
   125.1 2124.55   135.2  2124.2   144.9 2124.79   155.4    2127   168.8 2126.13
     175 2125.04   182.3 2122.82   185.6 2122.71   192.4 2123.63   195.7  2125.3
   202.4 2129.81   205.8  2131.4   209.2 2131.85   219.3  2131.6   229.4 2133.31
   236.1 2135.62   242.8 2139.15   256.3 2148.01   273.1 2161.74   280.2 2168.29
#Mann= 3 ,-1 , 0
       0      .1       0   125.1    .045       0   144.9      .1       0
#XS Ineff= 2 , 0
                          154.82         2128.18
Permanent Ineff=
       F       F
Bank Sta=125.1,144.9
XS Rating Curve= 0 ,0
Exp/Cntr=0.3,0.1

Type RM Length L Ch R = 1 ,12126   ,212,206.7,198.3
XS GIS Cut Line= 3
2011795.32802029262422.3716741832011726.61724167 262431.79989259
2011503.31886143262538.763271395
#Sta/Elev= 30
       0  2184.2    22.5 2173.69    40.3 2166.98    77.4 2146.26    91.3 2139.35
   128.3 2125.08   135.4 2123.43   153.8 2120.75     172 2116.74   179.3 2114.12
   196.2 2116.31   199.5 2115.77   203.8 2114.09   209.4 2113.13   222.9 2113.65
   226.6 2114.81   226.6 2114.82     229 2118.22   233.9 2128.29   244.8 2142.97
   248.7 2147.61   256.9 2154.58   263.5 2161.21   270.2 2166.53   275.4 2172.52
   283.1 2179.97     292  2190.3   295.4 2192.81     303 2197.05   316.9 2208.28
#Mann= 3 ,-1 , 0
       0      .1       0   203.8    .045       0   226.6      .1       0
Bank Sta=203.8,226.6
XS Rating Curve= 0 ,0
Exp/Cntr=0.3,0.1

Type RM Length L Ch R = 1 ,11920   ,181.4,183.9,185.4
XS GIS Cut Line= 3
2011646.63715298 262227.637738342011567.97356873262263.146545292
2011441.94597992262407.797647177
#Sta/Elev= 30
       0 2152.95     7.4 2150.71    21.7 2147.87      39 2143.31    55.3 2139.79
    99.8 2132.98   104.2  2131.9   108.5 2129.26   116.5 2121.84   125.6  2114.8
   134.6 2102.91   137.4 2101.17   140.6 2100.25   147.7 2100.16   156.4 2100.38
   160.5 2101.42   169.4 2104.66   172.3 2105.16   181.6 2104.17   195.5 2105.84
   204.8 2106.51   210.5 2108.29   221.7 2113.21   239.7 2123.38   256.5 2134.71
   260.4 2137.65   265.4  2142.7   272.3  2148.8   273.9 2150.67   278.2 2157.14
#Mann= 3 ,-1 , 0
       0      .1       0   137.4    .045       0   160.5      .1       0
Bank Sta=137.4,160.5
XS Rating Curve= 0 ,0
Exp/Cntr=0.3,0.1

Type RM Length L Ch R = 1 ,11736   ,173.9,167.5,163.7
XS GIS Cut Line= 3
2011528.60437223262137.7144541282011437.96366402 262147.78564393
 2011296.9670068262266.808796128
#Sta/Elev= 30
       0 2149.41    22.7 2143.37    35.9 2140.84    42.5 2139.21    55.7 2135.41
    65.6 2131.99    75.5 2127.22    85.4 2121.67    88.7 2120.07   112.9 2109.91
     118 2106.79   130.8 2097.12   133.3 2096.02   141.3 2093.32   148.2 2091.82
   152.9 2092.12   156.6 2093.11   163.8 2094.62   169.5 2096.45   173.8 2096.62
   182.4 2095.48   190.2 2097.29   199.5 2097.39   201.8  2097.8   203.8 2098.51
   216.7 2107.85   240.1 2122.73   246.8 2127.33   263.9 2140.02   275.7 2148.46
#Mann= 3 ,-1 , 0
       0      .1       0   141.3    .045       0   156.6      .1       0
#XS Ineff= 2 , 0
                          173.58         2097.99
Permanent Ineff=
       F       F
Bank Sta=141.3,156.6
XS Rating Curve= 0 ,0
Exp/Cntr=0.3,0.1

Type RM Length L Ch R = 1 ,11568   ,254.8,250.9,248.1
XS GIS Cut Line= 2
2011362.21089597261929.1417231772011195.42885161262201.411195548
#Sta/Elev= 30
       0 2130.06    19.2    2123      24 2121.92    57.4  2111.1    66.9  2105.9
    76.6 2101.75    83.6 2098.01    90.8  2095.4   102.7 2089.15   112.3 2088.31
   121.8 2086.55   133.7 2087.94   138.2 2087.82   145.4 2084.28   157.4 2081.66
   165.1 2082.48   168.9 2083.92   176.6 2088.83   188.2 2091.25     192 2092.94
   203.6 2100.44   212.5 2107.32     219 2110.12   229.2 2115.87   245.9 2123.11
   257.4 2126.98   276.7 2136.35   289.8 2143.82   299.8  2148.7   319.3 2160.23
#Mann= 3 ,-1 , 0
       0      .1       0   145.4    .045       0   168.9      .1       0
Bank Sta=145.4,168.9
XS Rating Curve= 0 ,0
Exp/Cntr=0.3,0.1

Type RM Length L Ch R = 1 ,11317   ,162.7,179.3,188.3
XS GIS Cut Line= 3
2011172.47119528261820.9907323292011082.08704161261870.291160603
2011012.01392067262075.718857402
#Sta/Elev= 30
       0 2121.24      15 2116.38    23.6 2114.34    42.3 2111.31    63.3 2107.05
   116.3 2099.17     144 2086.96     151 2083.23   154.4 2082.77   164.8 2082.65
   178.7  2083.8   182.1 2082.94   192.4 2076.28   203.4 2074.54   206.4  2073.5
   215.7 2073.86   227.2 2073.38   230.7 2073.43   237.6  2074.8   241.1 2076.36
   244.6 2079.25   258.4 2092.03   267.4  2102.1   282.7 2116.85   287.5  2123.8
   295.8  2133.6   303.3 2141.41   310.4 2147.65     314 2150.34     320  2156.2
#Mann= 3 ,-1 , 0
       0      .1       0   203.4    .045       0   237.6      .1       0
#XS Ineff= 2 , 0
          198.96 2078.09
Permanent Ineff=
       F       F
Bank Sta=203.4,237.6
XS Rating Curve= 0 ,0
Exp/Cntr=0.3,0.1