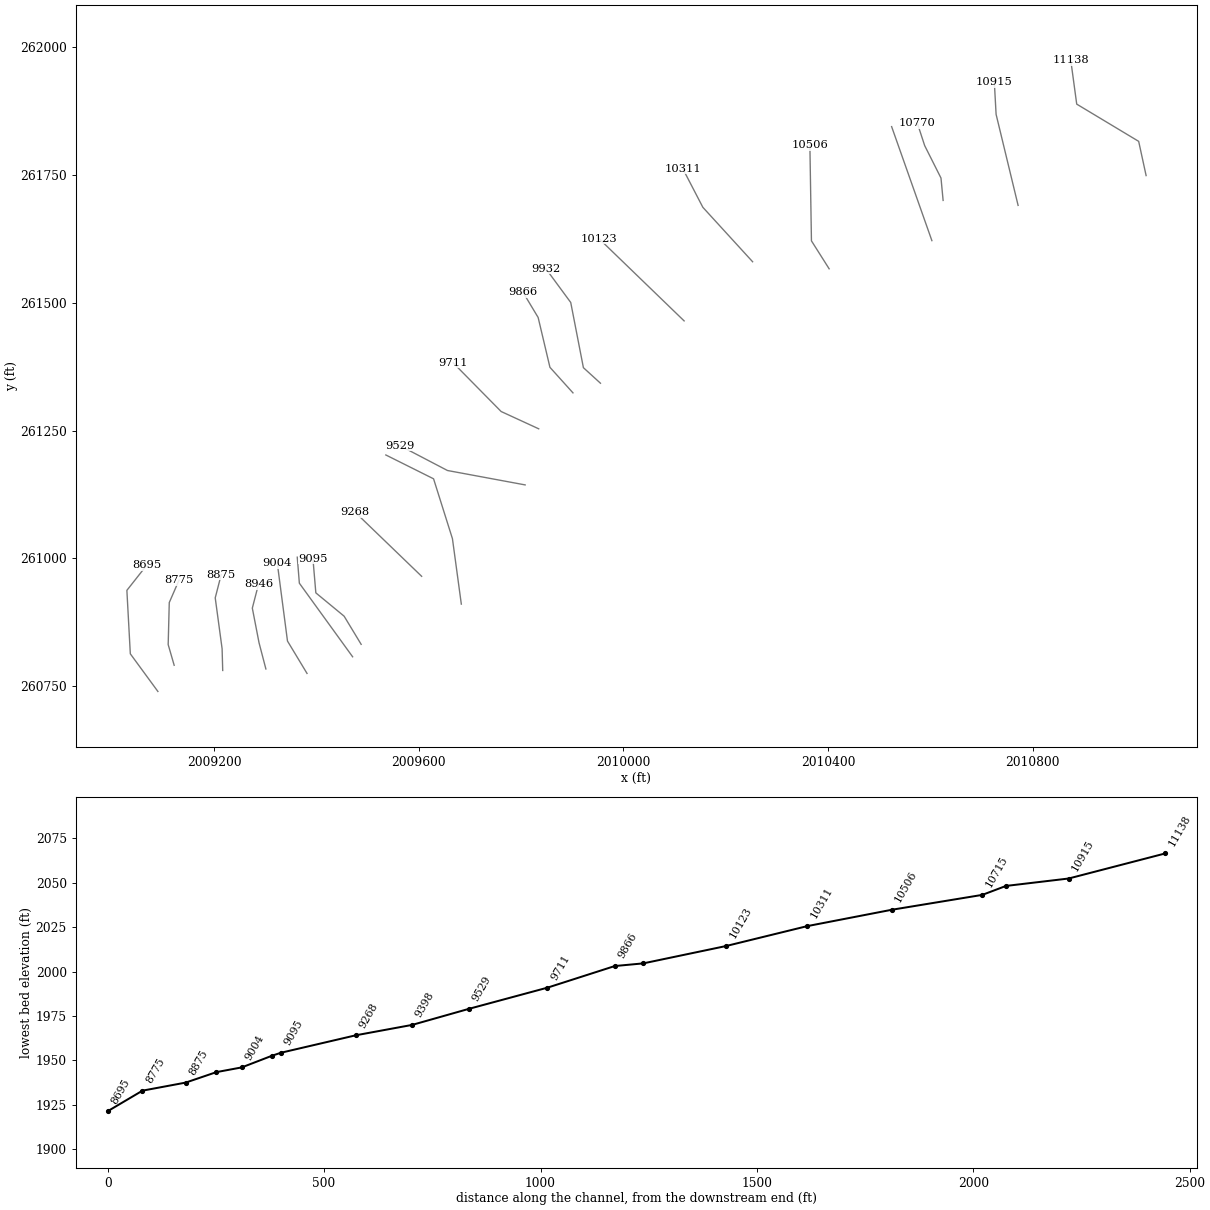
HEC-RAS study BRKSBR_A.prj: BRKSBR_A

--- BRKSBR_A.g01 (geometry) --- (continued)

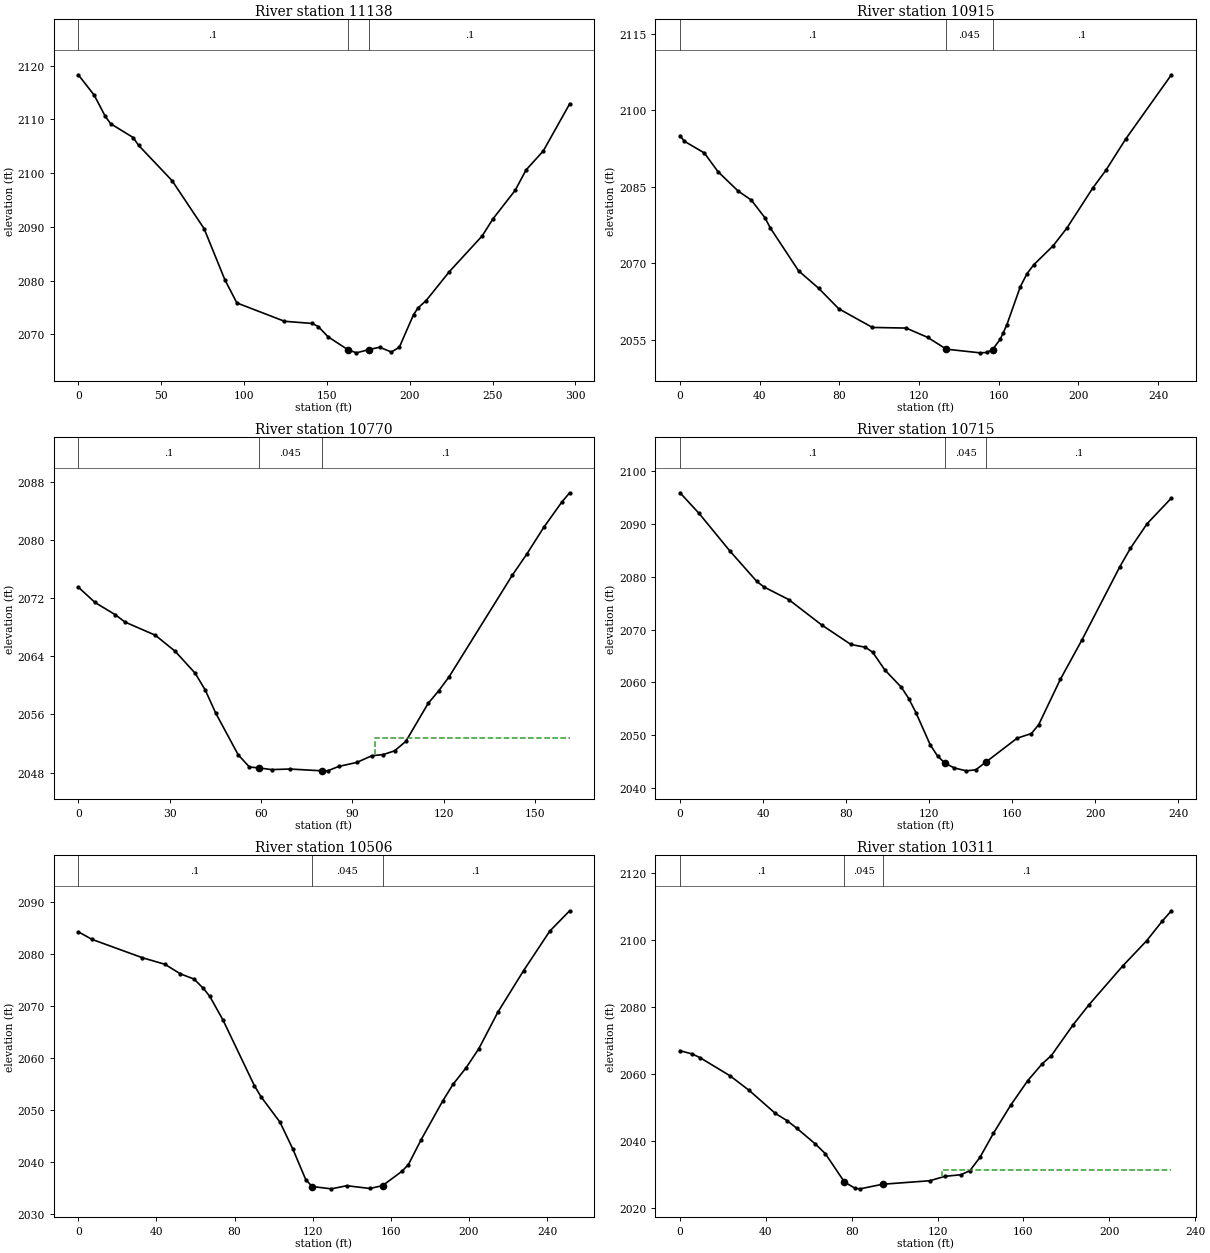
Type RM Length L Ch R = 1 ,11138   ,227.8,223.5,212.4
XS GIS Cut Line= 4
2011021.73708432261748.9076976532011007.19177517261815.876002141
 2010886.0840674261888.7323409182010874.44321499261974.604089304
#Sta/Elev= 30
       0 2118.29     9.6  2114.5    16.3 2110.55    19.6 2109.17    33.1 2106.62
    36.4 2105.16    56.6  2098.6    75.9 2089.68    88.5 2080.13    95.7 2075.86
   124.4 2072.45   141.3 2072.04   144.9 2071.44   150.7 2069.57   162.6 2067.18
   167.8 2066.58   175.5 2067.19   181.8 2067.62   188.9 2066.74   193.7 2067.61
   202.3 2073.68     205 2074.93   209.9  2076.3   223.9 2081.68   243.7 2088.32
   250.3 2091.53   263.6 2096.79   270.2 2100.59   280.6 2104.13   296.5 2112.88
#Mann= 3 ,-1 , 0
       0      .1       0   162.6    .045       0   175.5      .1       0
Bank Sta=162.6,175.5
XS Rating Curve= 0 ,0
Exp/Cntr=0.3,0.1

Type RM Length L Ch R = 1 ,10915   ,140,144.7,147.7
XS GIS Cut Line= 3
2010771.47364022261690.6025342492010728.46665337261868.737663171
2010724.99449848261932.084959482
#Sta/Elev= 30
       0 2095.05     2.1 2093.95    12.2 2091.63      19 2087.99    29.1 2084.19
    35.8 2082.38    42.6 2078.94    45.4 2076.88    59.5 2068.52    69.6 2065.09
    79.7 2061.07    96.6 2057.41   113.5 2057.29   124.3 2055.47   133.7 2053.15
   150.6 2052.43     154  2052.5   156.9 2053.07   160.7 2055.06   162.3 2056.39
   164.1 2057.95   170.8 2065.36   174.2 2067.96   177.6 2069.71   187.3 2073.42
   194.2 2076.89   207.3  2084.8   213.9 2088.29   223.7 2094.34   246.7 2106.97
#Mann= 3 ,-1 , 0
       0      .1       0   133.7    .045       0   156.9      .1       0
Bank Sta=133.7,156.9
XS Rating Curve= 0 ,0
Exp/Cntr=0.3,0.1

Type RM Length L Ch R = 1 ,10770   ,56.5,54.6,52.6
XS GIS Cut Line= 4
 2010624.8932839261700.2961132652010620.74320319261744.031579151
2010588.81950546261807.5597376292010574.45384149261851.614440493
#Sta/Elev= 30
       0  2073.5     5.5 2071.39    12.1 2069.72    15.4 2068.69    25.3 2066.89
    31.8 2064.69    38.4 2061.66    41.7 2059.36    45.1 2056.22    52.5 2050.47
    56.2 2048.78    59.22048.657    63.5 2048.42    69.5  2048.5    79.92048.255
    81.9 2048.25    85.5 2048.85    91.5 2049.41    96.4 2050.32   100.2 2050.49
   103.9    2051   107.6 2052.31   114.9 2057.51   118.4 2059.26   121.8 2061.18
   142.5  2075.1   147.3 2078.03   152.9 2081.72   158.8 2085.18   161.4 2086.47
#Mann= 3 ,-1 , 0
       0      .1       0    59.2    .045       0    79.9      .1       0
#XS Ineff= 2 , 0
                           97.35         2052.75
Permanent Ineff=
       F       F
Bank Sta=59.2,79.9
XS Rating Curve= 0 ,0
Exp/Cntr(USF)=0,0
Exp/Cntr=0.3,0.1

Type RM Length L Ch R = 1 ,10715   ,212.7,209.3,197.9
XS GIS Cut Line= 2
 2010602.9129534261621.6200515872010524.22841758 261844.70963543
#Sta/Elev= 30
       0 2095.96     9.2 2092.03    24.1 2084.87      37 2079.13    40.5 2078.07
    52.3 2075.71    68.3 2070.86    82.3 2067.18    89.2 2066.66    92.7 2065.74
    98.6 2062.36   106.6 2059.05   110.1 2056.93   113.6 2054.25   120.5 2048.12
     124 2046.03   127.5 2044.68   132.1 2043.75   137.9 2043.21   142.4 2043.41
   147.5 2044.94   162.3  2049.4   169.2 2050.29   172.7 2051.97   183.1 2060.55
   193.6  2068.1   211.8 2081.95   216.9 2085.45   224.9 2090.09   236.6 2094.96
#Mann= 3 ,-1 , 0
       0      .1       0   127.5    .045       0   147.5      .1       0
Bank Sta=127.5,147.5
XS Rating Curve= 0 ,0
Exp/Cntr=0.3,0.1

Type RM Length L Ch R = 1 ,10506   ,184.5,195.3,209
XS GIS Cut Line= 3
2010402.07314868261566.4999245672010367.49208779261621.166685043
 2010364.4420331261808.066893126
#Sta/Elev= 30
       0 2084.27       7 2082.81    32.8 2079.28    44.4 2078.01    52.2 2076.19
    59.3 2075.17    64.1 2073.36    67.3 2071.86    74.1 2067.29    90.2 2054.64
    93.5 2052.57   103.3 2047.63   109.9 2042.44   116.5 2036.56   119.8 2035.26
   129.6 2034.82   137.5 2035.42   149.3 2034.89   155.8 2035.44   165.7 2038.19
     169 2039.47   175.5 2044.24   186.5 2051.66   191.9 2054.94   198.5 2058.07
   205.1 2061.79   214.9 2068.85     228 2076.79   241.4 2084.39   251.6 2088.31
#Mann= 3 ,-1 , 0
       0      .1       0   119.8    .045       0   155.8      .1       0
Bank Sta=119.8,155.8
XS Rating Curve= 0 ,0
Exp/Cntr=0.3,0.1

Type RM Length L Ch R = 1 ,10311   ,184.2,187.8,188.1
XS GIS Cut Line= 3
2010252.46847074261580.2829306482010155.22095397261686.779892912
2010116.24332401261761.927186396
#Sta/Elev= 30
       0 2066.94     5.5    2066     9.2 2064.91    23.3 2059.43    32.2 2055.07
    44.4 2048.18      50 2045.95    54.4 2043.73      63 2039.05    67.7 2036.12
    76.6 2027.63    81.6 2025.74    83.9  2025.6    94.4 2026.98   116.3 2028.02
   123.4 2029.34   130.9 2029.83     135 2031.03   139.7    2035     146 2042.24
     154  2050.6   161.9 2057.92   168.6 2062.95     173 2065.51   183.2 2074.77
   190.5 2080.69   206.2  2092.3   217.3 2099.81   224.7 2105.79   228.9 2108.83
#Mann= 3 ,-1 , 0
       0      .1       0    76.6    .045       0    94.4      .1       0
#XS Ineff= 2 , 0
                          122.25         2031.31
Permanent Ineff=
       F       F
Bank Sta=76.6,94.4
XS Rating Curve= 0 ,0
Exp/Cntr=0.3,0.1

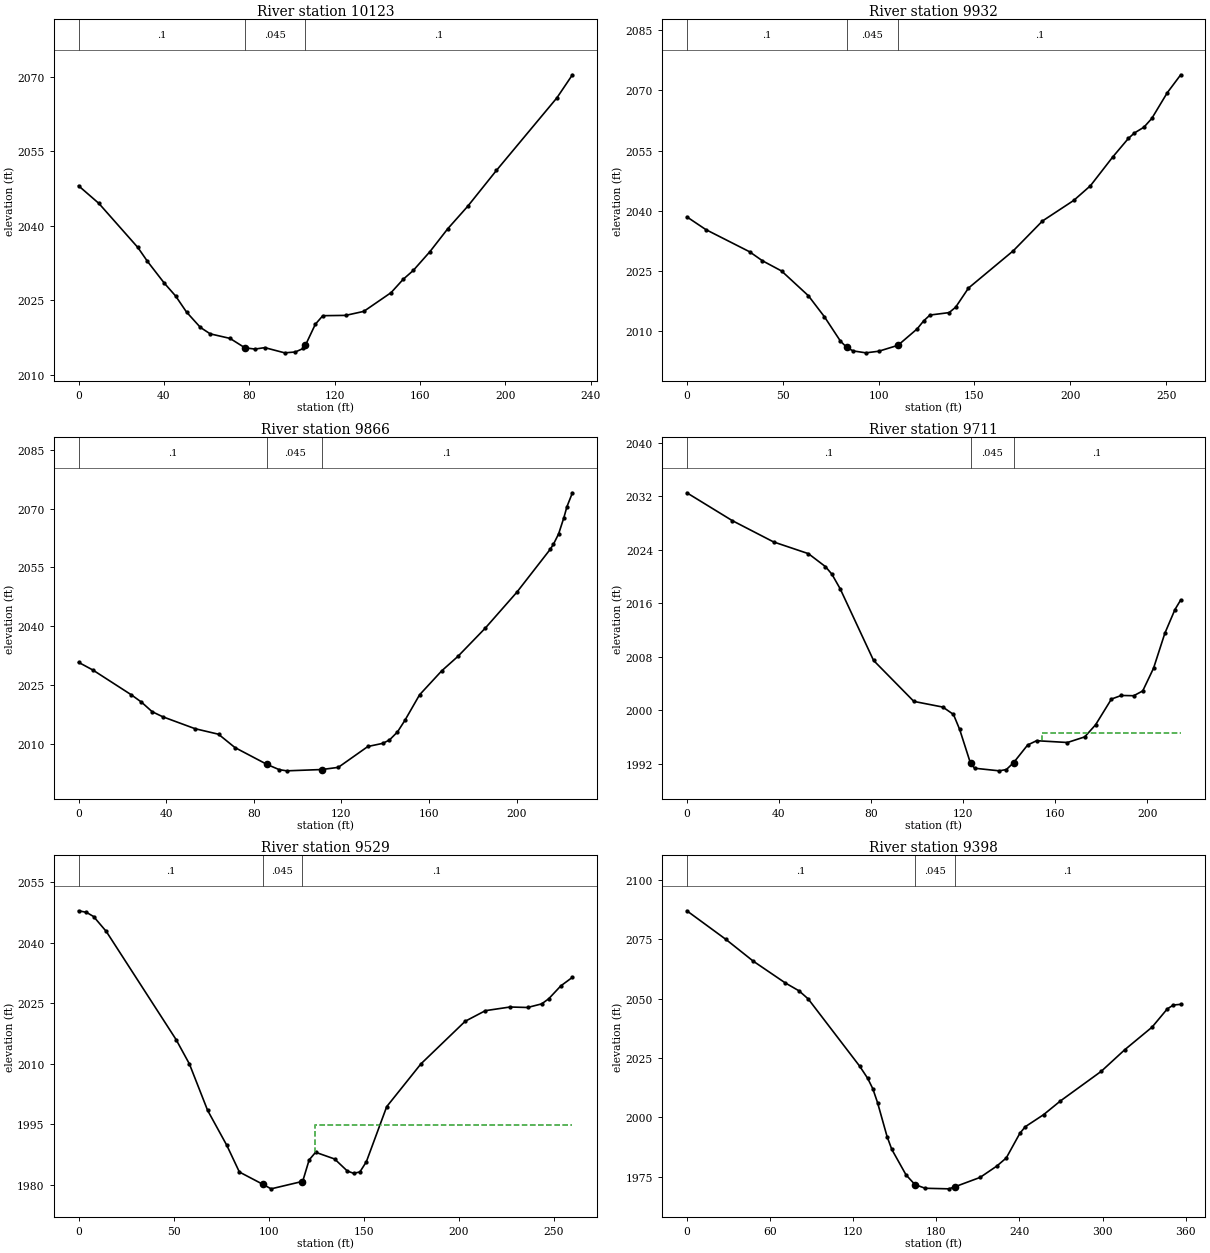
Type RM Length L Ch R = 1 ,10123   ,200.2,190.7,177.8
XS GIS Cut Line= 2
2010118.57821166 261464.520636312009952.18411956261625.508422173
#Sta/Elev= 30
       0 2048.05     9.5 2044.51    27.8 2035.61    32.3 2032.81    40.2 2028.42
    45.5 2025.83    50.6  2022.6    57.1  2019.5    61.7  2018.2      71 2017.28
      78 2015.38    82.7 2015.13    87.3 2015.42    96.6 2014.37   101.6 2014.54
   105.4 2015.27   106.3 2015.86     111 2020.14   114.5 2021.86   125.2 2021.92
   133.7 2022.73   146.5 2026.51   152.2 2029.21   156.9 2030.98   164.7 2034.77
   173.1 2039.41   182.4 2043.91   195.9 2051.16   224.2 2065.77   231.5 2070.43
#Mann= 3 ,-1 , 0
       0      .1       0      78    .045       0   106.3      .1       0
Bank Sta=78,106.3
XS Rating Curve= 0 ,0
Exp/Cntr=0.3,0.1

Type RM Length L Ch R = 1 ,9932    ,65.2,66,66.8
XS GIS Cut Line= 4
2009955.04377114261342.541414164 2009921.6787423261372.984747293
2009896.91965575261500.5626779212009848.10974425 261566.99603577
#Sta/Elev= 30
       0 2038.49     9.9 2035.32    32.7  2029.8    39.4 2027.56    49.4 2025.01
    63.4 2018.84    71.8 2013.58    80.1 2007.55    83.4 2005.98    86.7  2005.1
    93.4 2004.62   100.1 2005.02   110.1 2006.49   120.1 2010.57   123.5 2012.56
   126.8 2014.03   136.8 2014.64   140.2 2015.98   146.9 2020.75   170.3 2030.05
   185.5 2037.46   201.8 2042.58   210.5 2046.23   222.2 2053.43   230.3 2058.02
   233.4 2059.36   238.4 2060.81   242.5 2062.99   250.6 2069.41   257.6 2073.87
#Mann= 3 ,-1 , 0
       0      .1       0    83.4    .045       0   110.1      .1       0
Bank Sta=83.4,110.1
XS Rating Curve= 0 ,0
Exp/Cntr=0.3,0.1

Type RM Length L Ch R = 1 ,9866    ,145,155.4,163.5
XS GIS Cut Line= 4
2009901.30903294261323.6583424632009856.26114837261373.672135568
2009833.20514446261471.2167675122009803.40969325261520.875852865
#Sta/Elev= 30
       0 2030.79     6.5 2028.84    24.1  2022.5    28.7 2020.65    33.6  2018.2
    38.5 2016.89    53.2 2013.86    63.9 2012.45    71.4 2009.05    86.12004.733
    91.6 2003.42      95 2003.11   111.22003.449   118.6    2004   132.1 2009.32
   138.8 2010.11   141.9 2010.95   145.6 2013.02     149 2015.98   155.7  2022.5
   165.8 2028.61   173.2  2032.3   185.7 2039.51   200.1 2048.66   215.3 2059.58
   216.8 2060.88   219.2 2063.57   221.6 2067.71     223 2070.51   225.5 2074.04
#Mann= 3 ,-1 , 0
       0      .1       0    86.1    .045       0   111.2      .1       0
Bank Sta=86.1,111.2
XS Rating Curve= 0 ,0
Exp/Cntr(USF)=0,0
Exp/Cntr=0.3,0.1

Type RM Length L Ch R = 1 ,9711    ,164.7,181.5,183.4
XS GIS Cut Line= 3
2009834.31798029261253.334271581 2009760.8541068261287.195768652
2009667.08797021261382.399519954
#Sta/Elev= 30
       0 2032.55    19.7 2028.39    37.7 2025.19    52.8 2023.44    60.2  2021.5
      63 2020.37    66.6 2018.18    81.1 2007.46    98.6 2001.33   111.2 2000.48
   115.8 1999.38   118.5 1997.13   123.2 1992.07     125 1991.33   135.7 1990.94
   138.8 1991.14   141.9 1992.16     148  1994.8   151.9 1995.45   165.3 1995.18
   172.8 1996.02   177.5 1997.82   184.4 2001.68   188.7 2002.22   194.1 2002.18
     198  2002.9   202.7  2006.3   207.6 2011.52     212 2015.08   214.5 2016.51
#Mann= 3 ,-1 , 0
       0      .1       0   123.2    .045       0   141.9      .1       0
#XS Ineff= 2 , 0
                          154.37         1996.66
Permanent Ineff=
       F       F
Bank Sta=123.2,141.9
XS Rating Curve= 0 ,0
Exp/Cntr=0.3,0.1

Type RM Length L Ch R = 1 ,9529    ,143.3,131.1,101.9
XS GIS Cut Line= 3
2009807.80952424261143.555661529  2009655.899802261171.767467096
2009562.58382979261220.595592096
#Sta/Elev= 30
       0 2047.92     4.1 2047.54     7.9  2046.5    14.6 2042.79    51.3    2016
    58.3 2009.97    67.9 1998.44      78 1989.77    84.6 1983.17    96.91980.133
   101.3    1979   117.4  1980.8     118    1981   121.3 1986.17   124.7 1988.06
   134.7  1986.4   141.4 1983.41   144.7 1982.85     148 1983.19   151.4 1985.72
   162.1 1999.37   180.1 2009.97   203.4 2020.54     214 2023.16     227 2024.07
   236.2 2023.95   243.6 2024.84   247.3  2026.1   253.7 2029.31   259.8 2031.43
#Mann= 3 ,-1 , 0
       0      .1       0    96.9    .045       0   117.4      .1       0
#XS Ineff= 2 , 0
                          124.58         1994.93
Permanent Ineff=
       F       F
Bank Sta=96.9,117.4
XS Rating Curve= 0 ,0
Exp/Cntr(USF)=0,0
Exp/Cntr=0.3,0.1

Type RM Length L Ch R = 1 ,9398    ,118.5,130.1,138.2
XS GIS Cut Line= 4
2009683.02653813260910.2657309922009665.66542703 261038.30392544
2009628.77306587 261155.491425442009535.45709366261202.149411529
#Sta/Elev= 30
       0 2086.92      28 2074.97    47.9 2065.74    71.1 2056.55      81 2053.23
    87.6 2049.83   124.8 2021.49   130.5 2016.44   134.2 2012.07   137.6 2006.26
   144.5 1991.94   147.9 1986.54   158.2  1975.8   164.61971.747     172 1970.19
   189.2 1969.95   193.51970.829   211.6 1974.75   223.6 1979.49   230.5 1982.93
   240.3 1993.29   244.2 1996.07   257.4 2001.13   269.6 2006.93     299 2019.36
     316 2028.46   335.7 2037.96   346.7 2045.64   351.1 2047.28   356.4 2047.56
#Mann= 3 ,-1 , 0
       0      .1       0   164.6    .045       0   193.5      .1       0
Bank Sta=164.6,193.5
XS Rating Curve= 0 ,0
Exp/Cntr(USF)=0,0
Exp/Cntr=0.3,0.1

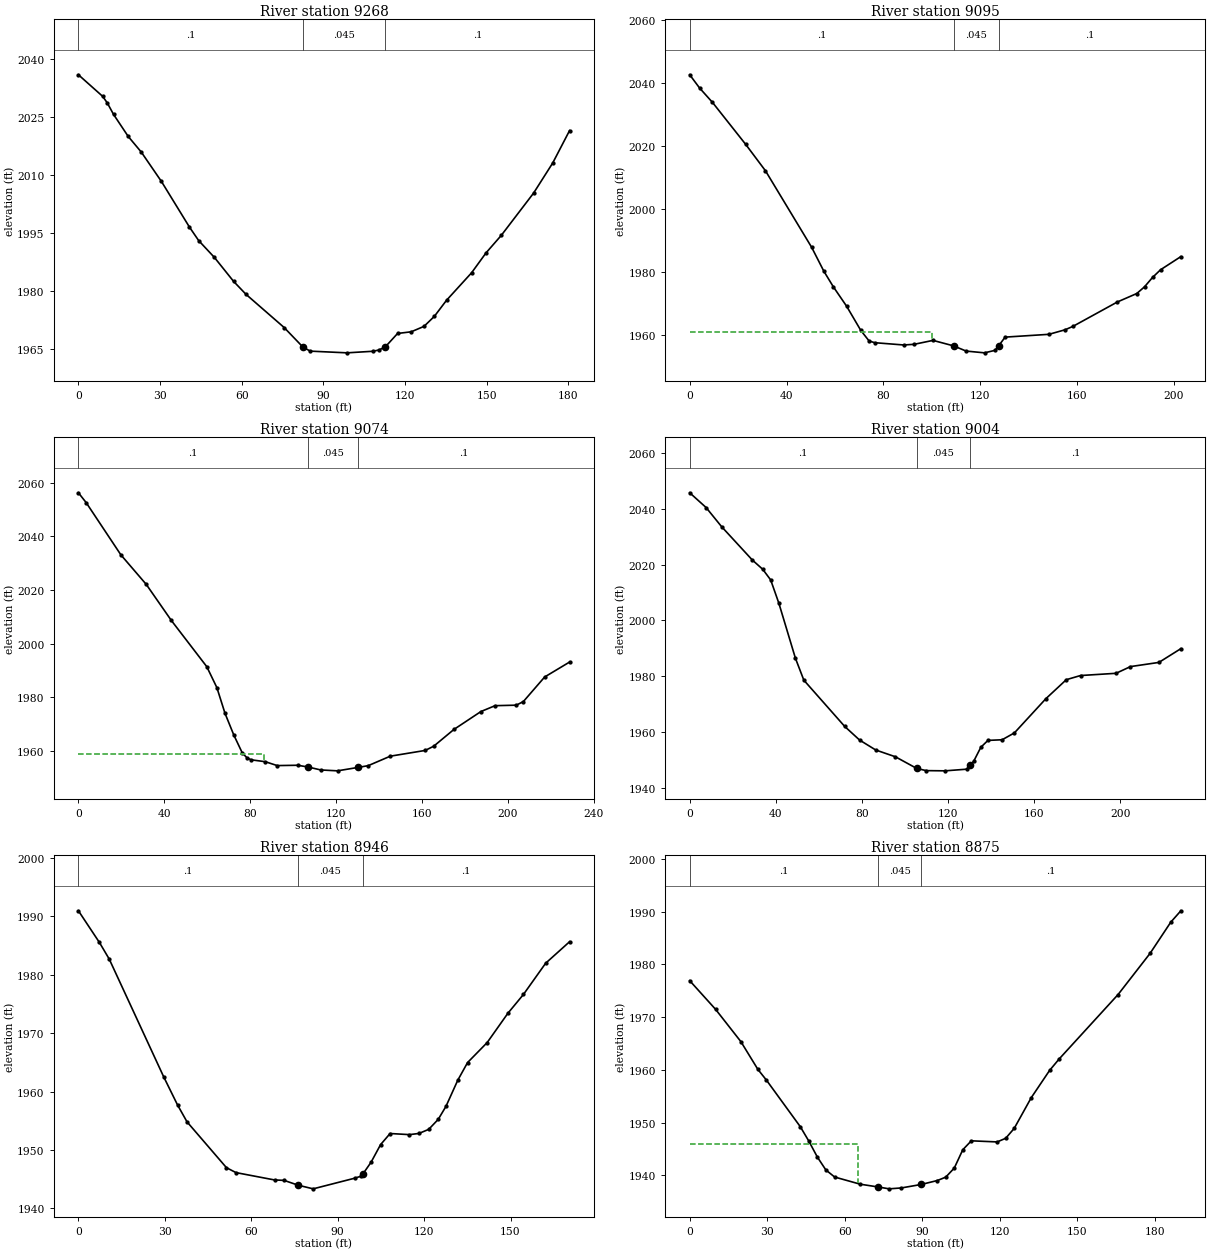
Type RM Length L Ch R = 1 ,9268    ,171.1,173.2,172.7
XS GIS Cut Line= 2
2009605.46599935260964.6862171882009475.57807862261089.996435452
#Sta/Elev= 30
       0 2035.99     8.9 2030.42    10.6 2028.73    12.9 2025.76    18.3 2020.05
    23.1 2016.01    30.5 2008.42    40.8 1996.62    44.2 1993.12      50 1988.75
      57  1982.6    61.6 1979.22    75.6 1970.65    82.5  1965.6    85.2 1964.54
    98.7  1964.1   108.1  1964.5   110.4 1964.82   112.8 1965.65   117.3 1969.11
   122.3 1969.54     127 1970.94   130.8 1973.52   135.3  1977.7   144.5  1984.8
   149.8 1989.94   155.4 1994.46   167.3 2005.42   174.3 2013.17   180.5 2021.56
#Mann= 3 ,-1 , 0
       0      .1       0    82.5    .045       0   112.8      .1       0
Bank Sta=82.5,112.8
XS Rating Curve= 0 ,0
Exp/Cntr=0.3,0.1

Type RM Length L Ch R = 1 ,9095    ,25.5,20.8,16.6
XS GIS Cut Line= 4
2009487.22316865260831.547716067 2009453.9203991260886.633429215
2009398.62523458260932.2938302272009392.97004729260998.899369318
#Sta/Elev= 30
       0 2042.69     4.1 2038.46     9.4 2033.91    23.1 2020.58    31.3 2012.15
    50.4 1987.78    55.4 1980.23    59.3 1975.29    64.8  1969.1    70.7 1961.36
    74.1 1958.03    76.4 1957.48    88.4 1956.75    92.7 1956.96   100.5 1958.21
     109 1956.47   114.2 1954.81   121.8 1954.25   126.1 1955.04   127.7 1956.56
   130.3 1959.25   148.4 1960.14     155 1961.57   158.3 1962.66   176.7 1970.44
   184.7 1973.12   187.9 1975.26   191.2 1978.23   194.5 1980.67   202.9 1984.86
#Mann= 3 ,-1 , 0
       0      .1       0     109    .045       0   127.7      .1       0
#XS Ineff= 2 , 0
          100.14  1960.8
Permanent Ineff=
       F       F
Bank Sta=109,127.7
XS Rating Curve= 0 ,0
Exp/Cntr(USF)=0,0
Exp/Cntr=0.3,0.1

Type RM Length L Ch R = 1 ,9074    ,77.8,69.6,61.4
XS GIS Cut Line= 3
2009470.52064129 260807.193259482009366.39518308260951.217257758
2009362.30580902261002.118733197
#Sta/Elev= 30
       0 2056.25     3.6  2052.6    19.8 2033.08    31.6 2022.09    43.3 2008.62
    59.8  1991.4    64.5 1983.59    68.3 1973.98    72.4 1965.89    76.4 1959.13
    78.6 1957.37    80.5 1956.66    87.1 1955.95    92.6 1954.51   102.1 1954.63
   106.8 1954.01   112.9 1952.88   120.7 1952.55   130.3 1953.83     135 1954.48
   145.3 1958.02   161.5 1960.15   165.5 1961.72   174.9 1967.97   187.5 1974.66
   194.1 1976.85     204 1977.04   207.3  1978.4   217.2 1987.55   228.8 1993.12
#Mann= 3 ,-1 , 0
       0      .1       0   106.8    .045       0   130.3      .1       0
#XS Ineff= 2 , 0
           86.48 1958.69
Permanent Ineff=
       F       F
Bank Sta=106.8,130.3
XS Rating Curve= 0 ,0
Exp/Cntr=0.3,0.1

Type RM Length L Ch R = 1 ,9004    ,57.2,58.6,59.5
XS GIS Cut Line= 3
2009381.37723258 260774.63205044 2009343.1827881260838.000105992
2009323.21751034260990.777883768
#Sta/Elev= 30
       0 2045.84     7.6 2040.55    14.8 2033.68    29.1 2021.68    33.9 2018.38
    37.6 2014.55    41.4 2006.19    49.1 1986.42      53 1978.56      72 1961.93
    78.9 1957.05    86.4 1953.48    95.5 1951.06   105.4 1946.88   109.8 1946.08
   118.6    1946   128.6 1946.59   130.3 1948.05   131.9 1949.45   135.2 1954.45
   138.5 1956.93   145.1 1957.16   150.8 1959.63   165.4  1971.9   174.9 1978.73
   181.5 1980.22     198 1981.02   204.7 1983.43   217.9 1984.93   228.1 1989.87
#Mann= 3 ,-1 , 0
       0      .1       0   105.4    .045       0   130.3      .1       0
Bank Sta=105.4,130.3
XS Rating Curve= 0 ,0
Exp/Cntr(USF)=0,0
Exp/Cntr=0.3,0.1

Type RM Length L Ch R = 1 ,8946    ,72.5,70.9,70.4
XS GIS Cut Line= 4
2009300.95726244260783.3569026962009287.54930939260834.754056052
2009274.46059332260902.4322952522009286.59159846260949.360130924
#Sta/Elev= 30
       0 1990.94     7.3 1985.51    10.7 1982.67    29.6 1962.52    34.4 1957.71
    37.7 1954.81    51.4 1946.96    54.7 1946.12    68.1 1944.86    71.4 1944.79
    76.3 1943.96    81.5 1943.34    95.9 1945.16    98.2 1945.52    98.7 1945.84
   101.6  1947.9   104.9 1950.91   108.2 1952.81   114.9 1952.62   118.2 1952.82
   121.6 1953.52   124.9 1955.23   127.6 1957.46   131.7 1961.94   135.1 1964.96
   141.9 1968.38   149.1  1973.4   154.5 1976.62   162.2 1981.96   170.5 1985.64
#Mann= 3 ,-1 , 0
       0      .1       0    76.3    .045       0    98.7      .1       0
Bank Sta=76.3,98.7
XS Rating Curve= 0 ,0
Exp/Cntr(USF)=0,0
Exp/Cntr=0.3,0.1

Type RM Length L Ch R = 1 ,8875    ,102.2,99.8,97.5
XS GIS Cut Line= 4
2009216.56121719260780.4144826992009215.37927046260822.906054566
2009201.93534721260922.5097716152009213.65983716260968.095328042
#Sta/Elev= 30
       0 1976.93      10  1971.5    19.8 1965.37    26.4 1960.09    29.7 1958.06
    42.8 1949.23    46.1  1946.5    49.4 1943.47    52.7 1941.02    56.1 1939.68
      66 1938.32      731937.789    77.2 1937.44    81.9 1937.61    89.6 1938.27
    95.8 1939.01    99.1 1939.66   102.4 1941.38   105.7 1944.86     109 1946.55
     119 1946.34   122.3 1947.03   125.6 1948.91   132.2 1954.74   139.3 1959.91
     143 1962.08   165.8  1974.3   178.2 1982.12   186.2 1988.03   190.1 1990.19
#Mann= 3 ,-1 , 0
       0      .1       0      73    .045       0    89.6      .1       0
#XS Ineff= 2 , 0
              65    1946
Permanent Ineff=
       F       F
Bank Sta=73,89.6
XS Rating Curve= 0 ,0
Exp/Cntr=0.3,0.1

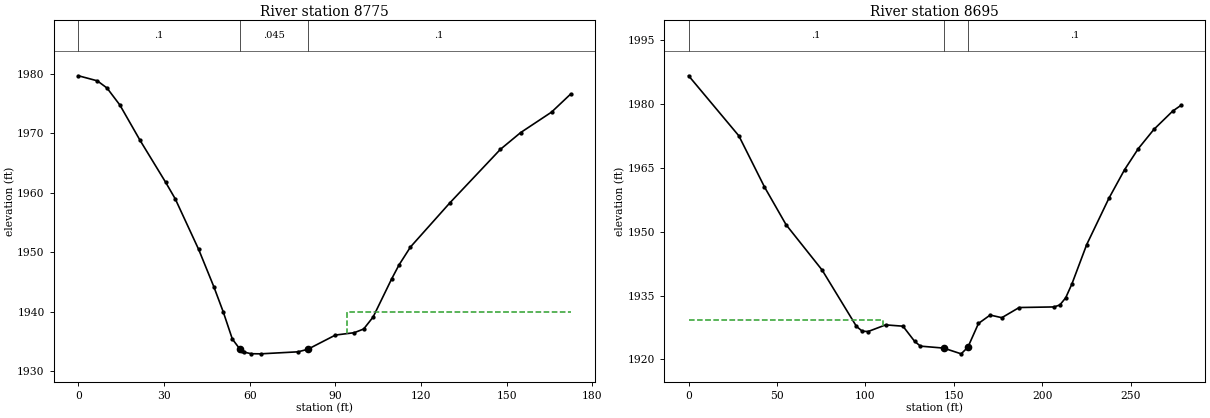
Type RM Length L Ch R = 1 ,8775    ,80,80.5,79.9
XS GIS Cut Line= 4
2009121.66611219260790.6164922632009109.96075635260831.053176051
2009112.08900287260913.3453746352009131.24322151260957.329135948
#Sta/Elev= 30
       0 1979.71     6.6 1978.86      10 1977.65    14.5 1974.79    21.6 1968.82
    30.5 1961.81    33.9 1958.99    42.1 1950.48    47.4 1944.22    50.7 1939.98
    53.9 1935.39    56.5 1933.73    57.2  1933.3    57.9  1933.2    60.5 1932.92
    63.8  1932.9    76.9 1933.24    80.3 1933.66      90 1936.06    96.6 1936.46
    99.9 1937.08   103.2 1939.09   109.7 1945.51   112.3 1947.88   116.3 1950.89
   130.1 1958.32   147.8 1967.33   154.9 1970.15   165.7 1973.59   172.4 1976.63
#Mann= 3 ,-1 , 0
       0      .1       0    56.5    .045       0    80.3      .1       0
#XS Ineff= 2 , 0
                              94            1940
Permanent Ineff=
       F       F
Bank Sta=56.5,80.3
XS Rating Curve= 0 ,0
Exp/Cntr(USF)=0,0
Exp/Cntr=0.3,0.1

Type RM Length L Ch R = 1 ,8695    ,83.4,88.3,90.8
XS GIS Cut Line= 4
2009089.85386509260739.3394019262009035.94389582260813.019107115
2009029.21787593260937.1936994342009068.00737873260986.392300759
#Sta/Elev= 30
       0 1986.68    28.4 1972.56    42.9 1960.53    55.1 1951.66    75.5 1940.99
    94.9 1927.75    98.2 1926.62   101.5 1926.55   111.4 1928.11   121.2  1927.8
   127.8 1924.23   131.1 1923.11   144.2 1922.65   154.1  1921.3   157.9 1922.86
   163.9 1928.45   170.5 1930.42   177.1  1929.8   186.9 1932.19   206.6 1932.33
   209.9 1932.79   213.2 1934.47   216.7 1937.71   225.1    1947   237.6 1957.84
   246.5  1964.6   254.3 1969.57   263.1 1974.08   273.7 1978.37   278.3  1979.7
#Mann= 3 ,-1 , 0
       0      .1       0   144.2    .045       0   157.9      .1       0
#XS Ineff= 2 , 0
          109.69 1929.23
Permanent Ineff=
       F       F
Bank Sta=144.2,157.9
XS Rating Curve= 0 ,0
Exp/Cntr=0.3,0.1