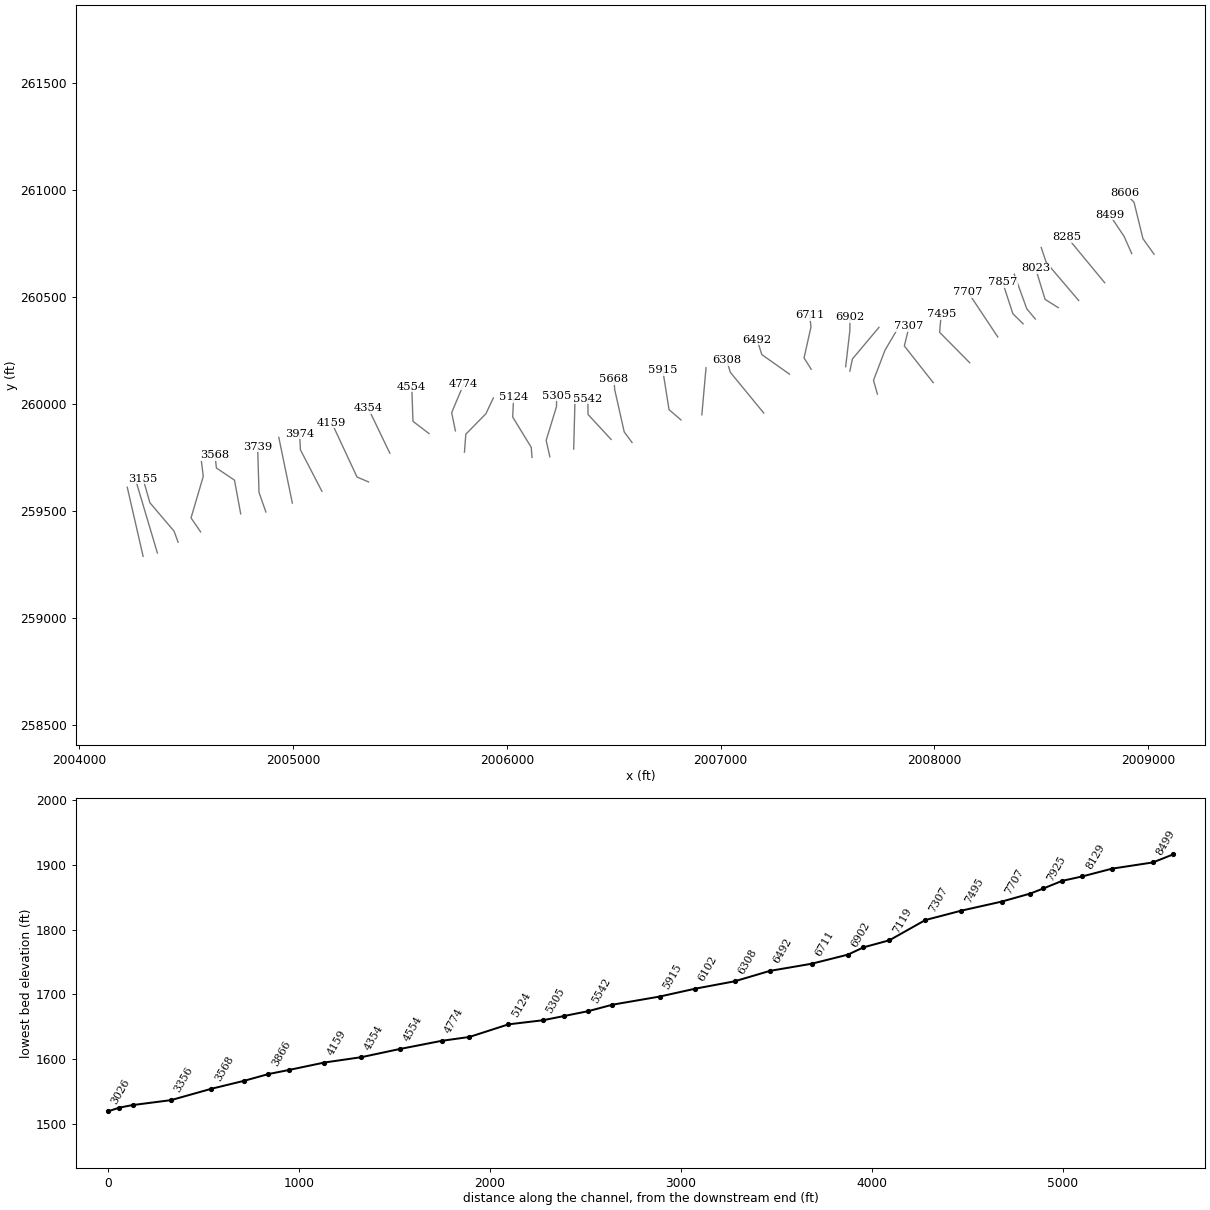
HEC-RAS study BRKSBR_A.prj: BRKSBR_A

--- BRKSBR_A.g01 (geometry) --- (continued)

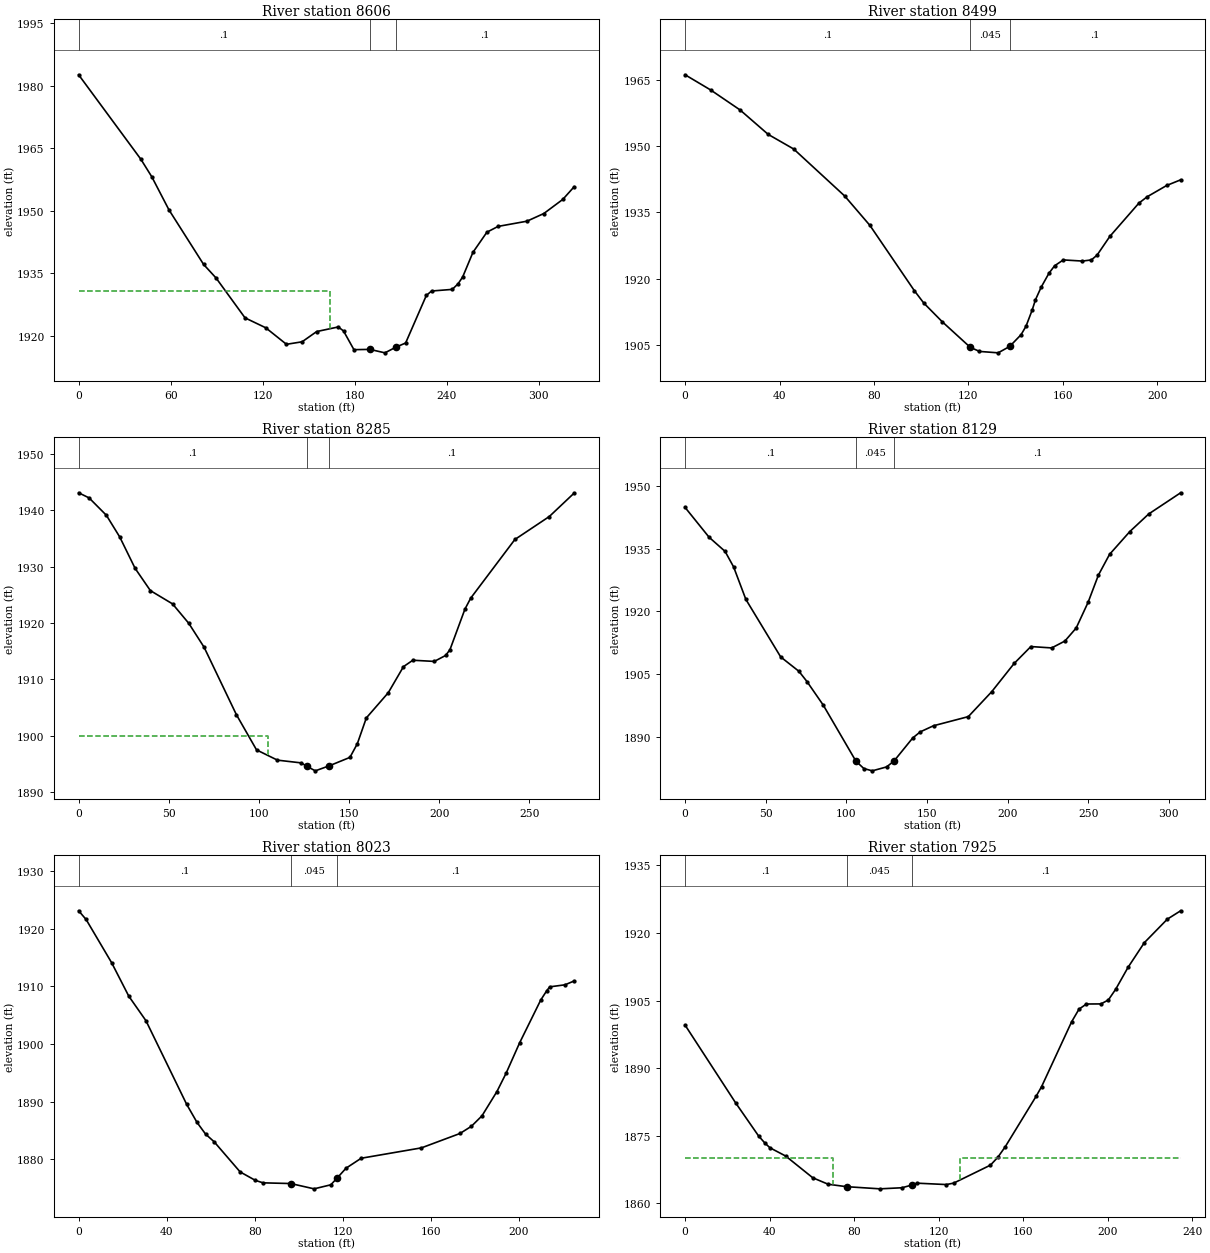
Type RM Length L Ch R = 1 ,8606    ,102,107.5,111.3
XS GIS Cut Line= 4
2009027.21056587260699.1112170822008975.12723255260772.027883768
2008933.46056587260942.1667726642008892.66195476 260983.83343932
#Sta/Elev= 30
       0 1982.64    40.6 1962.34    47.7 1958.14    58.9 1950.19    81.5 1937.08
    89.6 1933.83   108.5 1924.25     122 1921.87   135.5  1917.9   145.7  1918.5
   155.2 1920.96   169.3 1922.07   172.7 1921.11   179.5 1916.61   189.91916.679
   199.7 1915.85   206.91917.216   213.2 1918.21   226.7 1929.63   230.1  1930.7
   243.6 1931.09   247.4 1932.43   250.4 1934.07   257.1 1939.99   266.2 1944.83
   273.5 1946.22   292.3 1947.47   303.3 1949.31   315.7 1952.71   323.1 1955.75
#Mann= 3 ,-1 , 0
       0      .1       0   189.9    .045       0   206.9      .1       0
#XS Ineff= 2 , 0
          163.66 1930.72
Permanent Ineff=
       F       F
Bank Sta=189.9,206.9
XS Rating Curve= 0 ,0
Exp/Cntr(USF)=0,0
Exp/Cntr=0.3,0.1

Type RM Length L Ch R = 1 ,8499    ,212.2,213.7,215.3
XS GIS Cut Line= 3
2008922.57621783260702.4326994562008886.87591858260782.689405801
2008819.09547469 260884.23588064
#Sta/Elev= 30
       0 1966.08    10.8 1962.66    23.3 1958.13    35.2 1952.62      46 1949.32
    67.6 1938.71    78.3 1932.06    97.1 1917.34   101.1 1914.54   108.9 1910.33
   120.8 1904.54   124.7 1903.62   132.6  1903.3   137.5 1904.75   142.3 1907.39
   144.4  1909.3     147 1912.94   148.4 1915.27   150.8  1918.1   154.1 1921.25
   156.5 1922.95   160.2 1924.28   168.3 1924.02   172.1 1924.28   174.5 1925.36
   179.9 1929.58   192.2 1937.09   195.7 1938.53     204 1941.09   209.9 1942.36
#Mann= 3 ,-1 , 0
       0      .1       0   120.8    .045       0   137.5      .1       0
Bank Sta=120.8,137.5
XS Rating Curve= 0 ,0
Exp/Cntr=0.3,0.1

Type RM Length L Ch R = 1 ,8285    ,154.4,155.8,154.6
XS GIS Cut Line= 2
2008796.07116456260566.1172139592008620.99732223260778.022245762
#Sta/Elev= 30
       0 1943.13     5.8 1942.22    15.4 1939.13    22.8 1935.28    31.3 1929.72
    39.8 1925.75    52.1 1923.39    61.1 1919.94    69.6 1915.69    87.5 1903.72
    98.7 1897.45   110.3 1895.63   123.5 1895.14   126.6 1894.54   131.3 1893.73
     139 1894.62   150.5 1896.12   154.6 1898.54   159.6 1903.13   171.8 1907.62
   180.2 1912.24   185.4 1913.38   197.3 1913.17   203.6 1914.23     206 1915.26
   214.3 1922.46   217.5 1924.41     242 1934.83   261.1 1938.91   274.9 1943.08
#Mann= 3 ,-1 , 0
       0      .1       0   126.6    .045       0     139      .1       0
#XS Ineff= 2 , 0
             105    1900
Permanent Ineff=
       F       F
Bank Sta=126.6,139
XS Rating Curve= 0 ,0
Exp/Cntr=0.3,0.1

Type RM Length L Ch R = 1 ,8129    ,112.6,106.1,99.5
XS GIS Cut Line= 3
2008674.58490885260482.8176421972008522.77582959260660.901369797
2008499.42058662260730.480531127
#Sta/Elev= 30
       0 1944.93    14.9 1937.78    24.8  1934.4    30.1 1930.67    37.7 1922.88
    59.3 1909.09    70.6 1905.65    75.6 1903.19    85.7 1897.54     106 1884.08
   110.9 1882.33   116.1 1881.78     125 1882.72   129.6 1884.14   141.2 1889.66
   145.9 1891.13   154.1 1892.59   175.7 1894.78   190.2 1900.75   204.1 1907.52
   214.5 1911.58   227.4 1911.25   235.6  1912.9   242.6 1916.02     250 1922.19
   256.4 1928.72   263.3 1933.68   275.9 1939.16   287.6 1943.37   307.4 1948.45
#Mann= 3 ,-1 , 0
       0      .1       0     106    .045       0   129.6      .1       0
Bank Sta=106,129.6
XS Rating Curve= 0 ,0
Exp/Cntr=0.3,0.1

Type RM Length L Ch R = 1 ,8023    ,99.1,98.1,98.8
XS GIS Cut Line= 3
2008579.18893408260449.2557685222008517.31213725260488.273621299
2008472.77660832260633.703799833
#Sta/Elev= 30
       0 1923.09     3.4 1921.58      15 1914.09    22.8 1908.29    30.6 1904.04
    49.1 1889.55    53.8 1886.42    57.7 1884.39    61.6 1883.06    73.4 1877.84
    80.3 1876.38    83.8 1875.95    96.41875.828     107 1874.91   114.6 1875.61
   117.31876.705   121.5 1878.48   128.4 1880.21   155.8 1882.01   173.3  1884.5
   178.5 1885.75   183.3 1887.56   190.1 1891.77   194.3 1894.97   200.4  1900.2
     210 1907.62   212.7 1909.22   214.1 1909.91     221 1910.26   225.2 1910.93
#Mann= 3 ,-1 , 0
       0      .1       0    96.4    .045       0   117.3      .1       0
Bank Sta=96.4,117.3
XS Rating Curve= 0 ,0
Exp/Cntr(USF)=0,0
Exp/Cntr=0.3,0.1

Type RM Length L Ch R = 1 ,7925    ,70.4,68.2,69.4
XS GIS Cut Line= 3
2008471.71992663260396.2378399782008431.87004332260443.970117787
2008373.18999537260605.997115853
#Sta/Elev= 30
       0 1899.54    23.9  1882.3    34.8 1874.93    37.9  1873.3    40.2 1872.31
    47.6 1870.49    60.4 1865.67    67.7 1864.23    76.4 1863.69    92.2 1863.21
   102.6 1863.45   107.31864.049   109.7 1864.47   123.6 1864.16   127.1 1864.48
   144.5 1868.47     148 1870.22   151.5 1872.55   166.1 1883.74   168.7 1885.89
   182.9 1900.27   186.4 1903.08   189.9 1904.23   196.8 1904.25   200.3 1905.13
   203.8 1907.53   209.6 1912.36   217.3 1917.83   228.2 1923.06   234.5 1924.92
#Mann= 3 ,-1 , 0
       0      .1       0    76.4    .045       0   107.3      .1       0
#XS Ineff= 2 , 0
              70    1870     130            1870
Permanent Ineff=
       F       F
Bank Sta=76.4,107.3
XS Rating Curve= 0 ,0
Exp/Cntr(USF)=0,0
Exp/Cntr=0.3,0.1

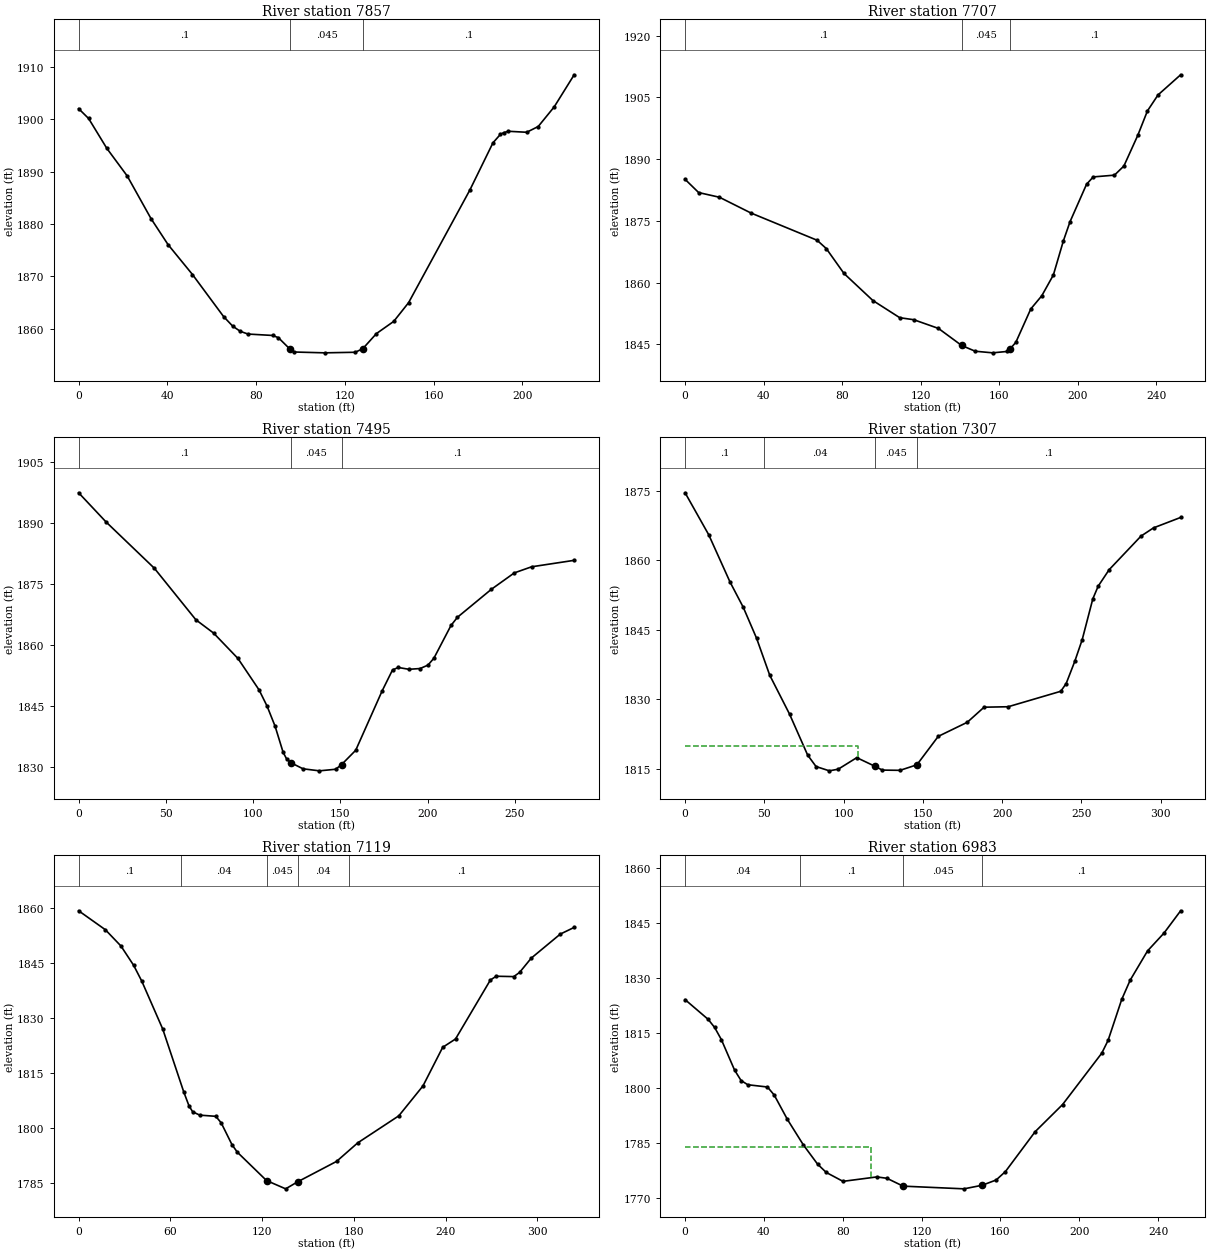
Type RM Length L Ch R = 1 ,7857    ,139.6,150.2,148.6
XS GIS Cut Line= 3
2008414.75578157260373.8407628532008366.62133329260421.198755897
2008318.39884346260569.325684549
#Sta/Elev= 30
       0 1902.02     4.5 1900.14    12.7 1894.44    21.9 1889.16    32.6 1881.03
    40.3 1876.05    51.3 1870.34    65.3 1862.32    69.4 1860.49    72.8  1859.5
    76.3 1858.97    87.4  1858.7      90 1858.28    95.4 1856.02      97 1855.54
   110.8 1855.38   124.6 1855.49     128 1856.15   134.2 1859.06     142 1861.39
   148.7 1864.97   176.3 1886.48   186.7 1895.49   190.1 1897.13   191.5 1897.42
   193.6  1897.7   201.9 1897.51   207.1 1898.61   214.3 1902.36   223.3 1908.49
#Mann= 3 ,-1 , 0
       0      .1       0    95.4    .045       0     128      .1       0
Bank Sta=95.4,128
XS Rating Curve= 0 ,0
Exp/Cntr=0.3,0.1

Type RM Length L Ch R = 1 ,7707    ,205.3,211.5,213
XS GIS Cut Line= 2
 2008296.3077881260312.2477911562008156.55084369260522.317235619
#Sta/Elev= 30
       0  1885.1     6.9 1881.89    17.5 1880.75    33.5 1876.93    67.2 1870.31
    71.9 1868.28    80.9 1862.24    95.6 1855.67   109.3 1851.49   116.4 1851.01
     129 1848.89   140.8 1844.75   147.7 1843.35   156.6 1842.96   163.8 1843.29
   165.21843.773   168.4 1845.52     176 1853.62   181.6 1856.82   187.5 1861.87
   192.6 1870.16     196 1874.83   204.4 1883.91   207.8 1885.69   218.6 1886.12
   223.4 1888.33   230.5 1895.81   235.4 1901.73   240.8 1905.61   252.3  1910.5
#Mann= 3 , 0 , 0
       0      .1       0   140.8    .045       0   165.2      .1       0
Bank Sta=140.8,165.2
XS Rating Curve= 0 ,0
Exp/Cntr(USF)=0,0
Exp/Cntr=0.3,0.1

Type RM Length L Ch R = 1 ,7495    ,190,188.5,185.5
XS GIS Cut Line= 3
2008164.80440181260191.9609537752008023.98367165260334.301347668
 2008031.5372941260417.698881801
#Sta/Elev= 30
       0 1897.43    15.7 1890.26    43.4 1878.86    67.2 1866.18    77.3 1862.93
    91.3 1856.67   103.4 1848.94     108 1844.94   112.6 1839.99   117.2 1833.57
   119.3 1831.87   121.9 1830.96   128.6 1829.52     138 1829.02   147.3 1829.41
   150.7 1830.56   158.8 1834.08   173.9 1848.65   179.9 1853.85   183.2 1854.45
   189.3    1854   195.7 1854.19   200.2 1855.03   203.6 1856.72   213.4 1864.78
   217.1  1866.8   236.5 1873.67   249.7 1877.72   259.6 1879.22     284 1880.81
#Mann= 3 ,-1 , 0
       0      .1       0   121.9    .045       0   150.7      .1       0
Bank Sta=121.9,150.7
XS Rating Curve= 0 ,0
Exp/Cntr=0.3,0.1

Type RM Length L Ch R = 1 ,7307    ,202.9,188,169.2
XS GIS Cut Line= 3
2007994.23506908260098.8482262482007859.09443343260270.324804787
2007881.55844424260361.900643584
#Sta/Elev= 30
       0 1874.62    14.9 1865.55    28.3 1855.37    36.7 1849.87    45.1 1843.18
    53.4 1835.19    65.9 1826.79    77.3 1817.95    82.6 1815.47      91 1814.54
    96.6  1814.9   108.3 1817.39   119.71815.535   124.4  1814.7   135.6 1814.65
   146.2 1815.84   159.7 1821.99     178 1825.03   188.6 1828.29   203.8 1828.39
     237 1831.73   240.4 1833.41   245.8 1838.18   250.5 1842.88   257.2  1851.7
   260.6 1854.45   267.5    1858   287.6 1865.26   295.5 1867.04   312.6 1869.29
#Mann= 4 ,-1 , 0
       0      .1       0      50     .04       0   119.7    .045       0
   146.2      .1       0
#XS Ineff= 2 , 0
          108.85    1820
Permanent Ineff=
       F       F
Bank Sta=119.7,146.2
XS Rating Curve= 0 ,0
Exp/Cntr=0.3,0.1

Type RM Length L Ch R = 1 ,7119    ,128.1,136.1,129.8
XS GIS Cut Line= 4
2007733.10306232260045.267886421 2007714.8968865260109.560309946
2007768.53945908260250.2941071952007822.70440561260342.132495503
#Sta/Elev= 30
       0 1859.32    17.5 1854.14    27.7 1849.69      36 1844.42    41.3 1840.11
      55 1827.04    68.7 1809.93    72.2 1806.04    74.6 1804.44    79.2 1803.53
    89.7 1803.21    93.2 1801.45   100.3 1795.47   103.8 1793.41   122.9 1785.67
   135.4 1783.41   143.3 1785.34   168.7  1790.9   182.5 1795.95   209.4 1803.34
   225.2  1811.5   238.1 1822.04   246.5 1824.32   269.3 1840.42   273.1 1841.45
   284.6 1841.35   288.4 1842.49     296 1846.38     315 1852.95   324.1 1854.78
#Mann= 5 ,-1 , 0
       0      .1       0   66.82     .04       0   122.9    .045       0
   143.3     .04       0  176.82      .1       0
Bank Sta=122.9,143.3
XS Rating Curve= 0 ,0
Exp/Cntr=0.3,0.1

Type RM Length L Ch R = 1 ,6983    ,53,80.8,84.1
XS GIS Cut Line= 3
2007604.29389924260152.3519578282007616.09945479 260209.29640229
2007740.40501031260357.213068947
#Sta/Elev= 30
       0 1824.06    11.7 1818.69      15 1816.47    18.4 1813.17    25.1 1804.86
    28.4 1802.02    31.8 1800.87    41.8 1800.25    45.2 1798.07    51.9 1791.42
      60 1784.47    67.2 1779.24    71.6 1776.97    80.1 1774.54    97.3 1775.75
   102.4 1775.37   110.61773.234   141.5  1772.5   150.8 1773.49   157.8 1774.91
   162.5  1777.2   177.6 1788.08   191.5 1795.47   211.4 1809.48   214.6 1812.97
   221.5 1824.11   225.8 1829.37   234.6 1837.34     243 1842.23   251.4 1848.28
#Mann= 4 ,-1 , 0
       0     .04       0   58.16      .1       0   110.6    .045       0
   150.8      .1       0
#XS Ineff= 2 , 0
            94.5 1783.79
Permanent Ineff=
       F       F
Bank Sta=110.6,150.8
XS Rating Curve= 0 ,0
Exp/Cntr(USF)=0,0
Exp/Cntr=0.3,0.1

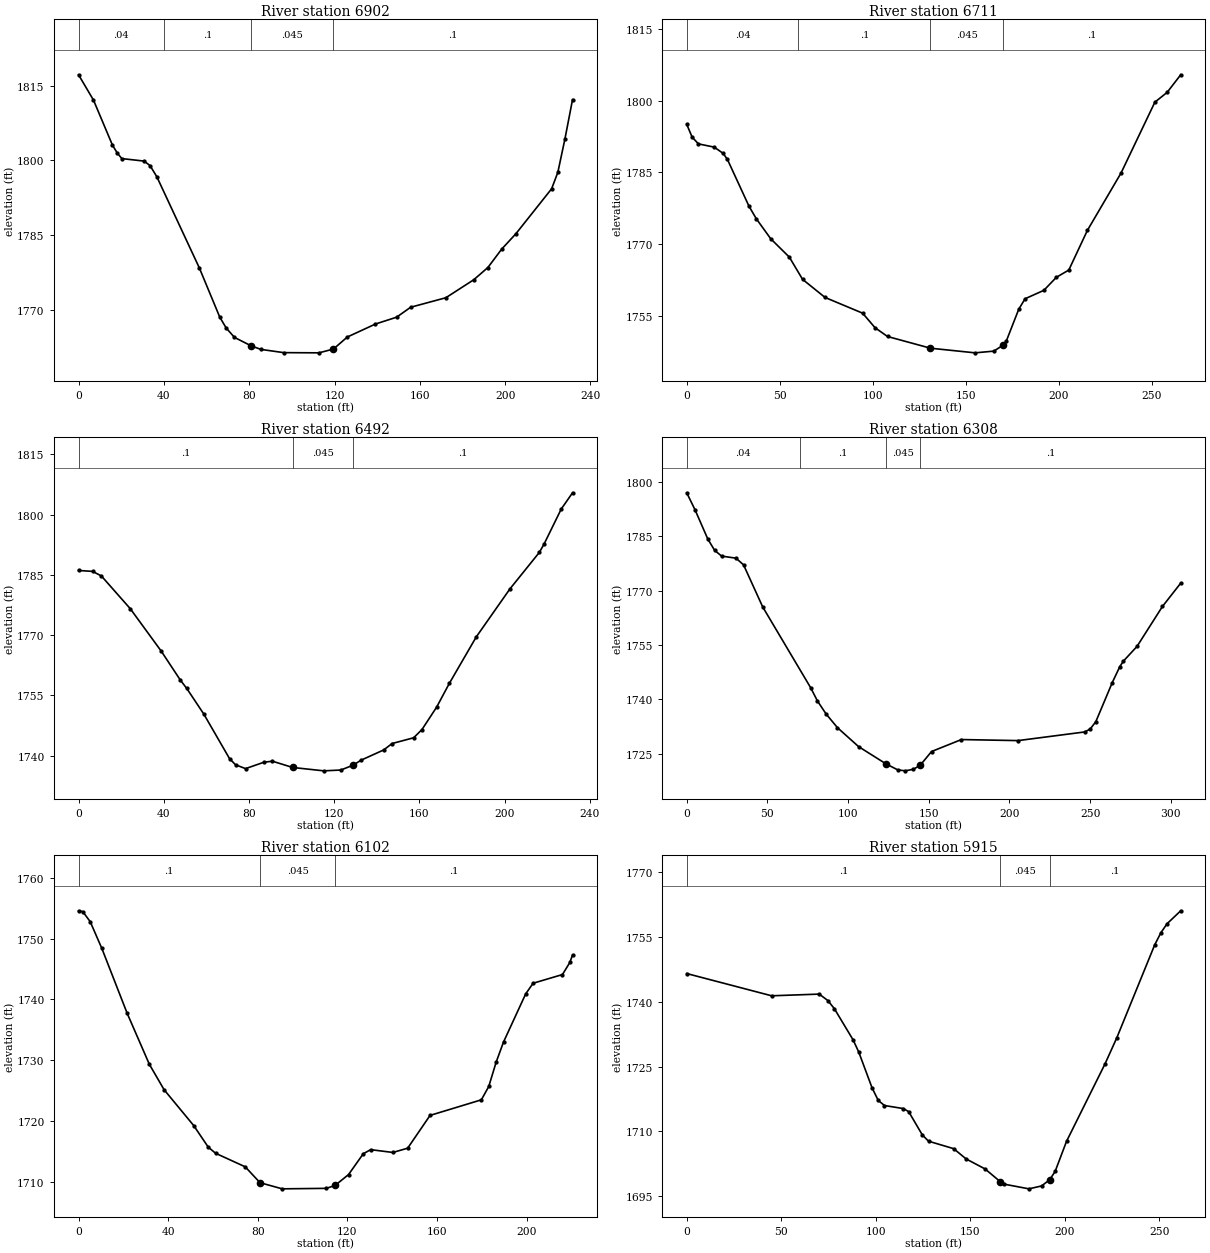
Type RM Length L Ch R = 1 ,6902    ,193.4,191,188.4
XS GIS Cut Line= 3
2007584.67629799260173.1659602032007604.38227025260343.041674972
2007604.90801931260403.633817418
#Sta/Elev= 30
       0 1817.18       7 1812.09    15.9 1803.04    18.2 1801.42    20.3 1800.34
    30.7 1799.84    33.5 1798.94    36.7 1796.69    56.6  1778.4    66.2 1768.49
    69.2 1766.31    73.1 1764.41      81  1762.7    85.5    1762    96.2 1761.35
   112.7 1761.31   119.5 1762.07     126 1764.49   139.2  1767.1   149.1 1768.47
   155.7 1770.47   172.2 1772.38   185.3    1776   191.9 1778.45   198.4 1782.16
     205 1785.22   221.8 1794.28   224.7 1797.57     228 1804.22   231.6  1812.2
#Mann= 4 ,-1 , 0
       0     .04       0      40      .1       0      81    .045       0
   119.5      .1       0
Bank Sta=81,119.5
XS Rating Curve= 0 ,0
Exp/Cntr=0.3,0.1

Type RM Length L Ch R = 1 ,6711    ,187,218.4,240.1
XS GIS Cut Line= 4
2007423.40554932260161.6896525782007390.00885836260214.297272473
2007422.34702965260358.5674088192007416.57898458260413.775840185
#Sta/Elev= 30
       0 1795.05     2.9 1792.38     6.3 1790.96    14.8 1790.28    19.6 1788.97
    21.9  1787.7    33.5 1777.91    37.4 1775.31    45.2  1771.1    55.2 1767.26
    62.3 1762.62    74.4 1758.83    94.6 1755.54   101.3 1752.49     108 1750.66
   131.1 1748.21   155.1 1747.24   165.2  1747.6   169.9 1748.79   171.9 1749.71
   178.6 1756.38     182 1758.56   192.1 1760.32   198.8 1763.04   205.5 1764.56
   215.5 1772.86   233.6 1784.86   251.8 1799.69   258.4 1801.74   265.7 1805.42
#Mann= 4 ,-1 , 0
       0     .04       0      60      .1       0   131.1    .045       0
   169.9      .1       0
Bank Sta=131.1,169.9
XS Rating Curve= 0 ,0
Exp/Cntr=0.3,0.1

Type RM Length L Ch R = 1 ,6492    ,188.2,184.3,179.7
XS GIS Cut Line= 3
2007321.88764383  260138.63539482007192.44923337260230.022404445
2007170.20105953  260300.0629517
#Sta/Elev= 30
       0 1786.12     6.6 1785.89    10.7 1784.76    24.3 1776.59    38.8 1766.05
    47.8 1758.82    50.8 1756.75    58.8 1750.37    70.9 1739.26    73.7 1737.75
    78.4 1736.79      87 1738.38      91 1738.64   100.5 1737.08   115.1 1736.24
   123.1 1736.44   128.9 1737.65   132.6 1738.89   143.2 1741.43   147.2 1743.04
   157.3 1744.47   161.2 1746.51   168.1  1752.1   174.1 1758.05   186.7 1769.58
   202.5 1781.53   216.3 1790.61   218.5 1792.66   226.6 1801.42   231.9 1805.46
#Mann= 3 ,-1 , 0
       0      .1       0   100.5    .045       0   128.9      .1       0
Bank Sta=100.5,128.9
XS Rating Curve= 0 ,0
Exp/Cntr=0.3,0.1

Type RM Length L Ch R = 1 ,6308    ,219.4,206.2,193.7
XS GIS Cut Line= 3
2007201.64216116259956.7992765012007045.12886439260147.287676263
2007027.97589258260204.316322249
#Sta/Elev= 30
       0 1797.02     5.2 1792.26    13.1 1784.21    17.3 1781.12    21.6 1779.54
    30.5 1778.96    35.2 1777.13    47.1 1765.48    76.8 1743.18      81 1739.52
    86.4 1735.91    93.4 1732.15   106.5 1726.92   123.5 1722.15   130.7 1720.51
   135.4 1720.23   140.5 1720.67   144.7 1721.78   151.7 1725.56   170.2 1728.87
   205.3 1728.58   246.6 1730.97     250 1731.78   253.5 1733.81   263.7 1744.62
   268.4 1749.04   270.6 1750.54     279 1754.58   294.8 1765.64   306.1 1772.06
#Mann= 4 ,-1 , 0
       0     .04       0      70      .1       0   123.5    .045       0
   144.7      .1       0
Bank Sta=123.5,144.7
XS Rating Curve= 0 ,0
Exp/Cntr=0.3,0.1

Type RM Length L Ch R = 1 ,6102    ,182.4,186.8,190.6
XS GIS Cut Line= 2
2006912.00711952259948.5716682922006931.55700694260168.206138704
#Sta/Elev= 30
       0 1754.57     1.9 1754.43     5.2 1752.78    10.4 1748.38    21.7 1737.72
    31.6 1729.34    38.2 1725.15    51.4 1719.27    57.9 1715.72    61.2 1714.71
    74.4 1712.49      81 1709.88    90.9 1708.87   110.6 1708.95   114.5 1709.43
   120.5 1711.21   127.1 1714.64   130.4 1715.31   140.3 1714.85   146.9 1715.55
   156.9 1720.94   179.8  1723.5   183.1 1725.69   186.4 1729.69   189.7 1733.01
   199.6 1740.92   202.9 1742.66     216 1744.09   219.3 1746.08   220.5 1747.31
#Mann= 3 ,-1 , 0
       0      .1       0      81    .045       0   114.5      .1       0
Bank Sta=81,114.5
XS Rating Curve= 0 ,0
Exp/Cntr=0.3,0.1

Type RM Length L Ch R = 1 ,5915    ,248,247.1,248.9
XS GIS Cut Line= 3
2006814.56011813259924.5436405512006758.49472007259972.599696033
2006729.21288349260157.779651877
#Sta/Elev= 30
       0 1746.54    44.9 1741.39    70.1 1741.78    74.7 1740.27    78.1  1738.4
      88 1731.19      91 1728.36      98 1720.12   101.3 1717.17   104.6 1715.99
   114.6 1715.28   117.4 1714.57   124.6  1709.2   127.9 1707.73   141.2    1706
   147.8 1703.62   157.8 1701.31   165.9 1698.34   167.7  1697.8     181  1696.7
   187.7 1697.37     192 1698.81   194.9 1700.76   200.9  1707.7   221.2 1725.57
   227.5 1731.67   247.5 1753.14   250.8 1755.98   254.1 1758.08   261.3 1761.07
#Mann= 3 ,-1 , 0
       0      .1       0   165.9    .045       0     192      .1       0
Bank Sta=165.9,192
XS Rating Curve= 0 ,0
Exp/Cntr=0.3,0.1

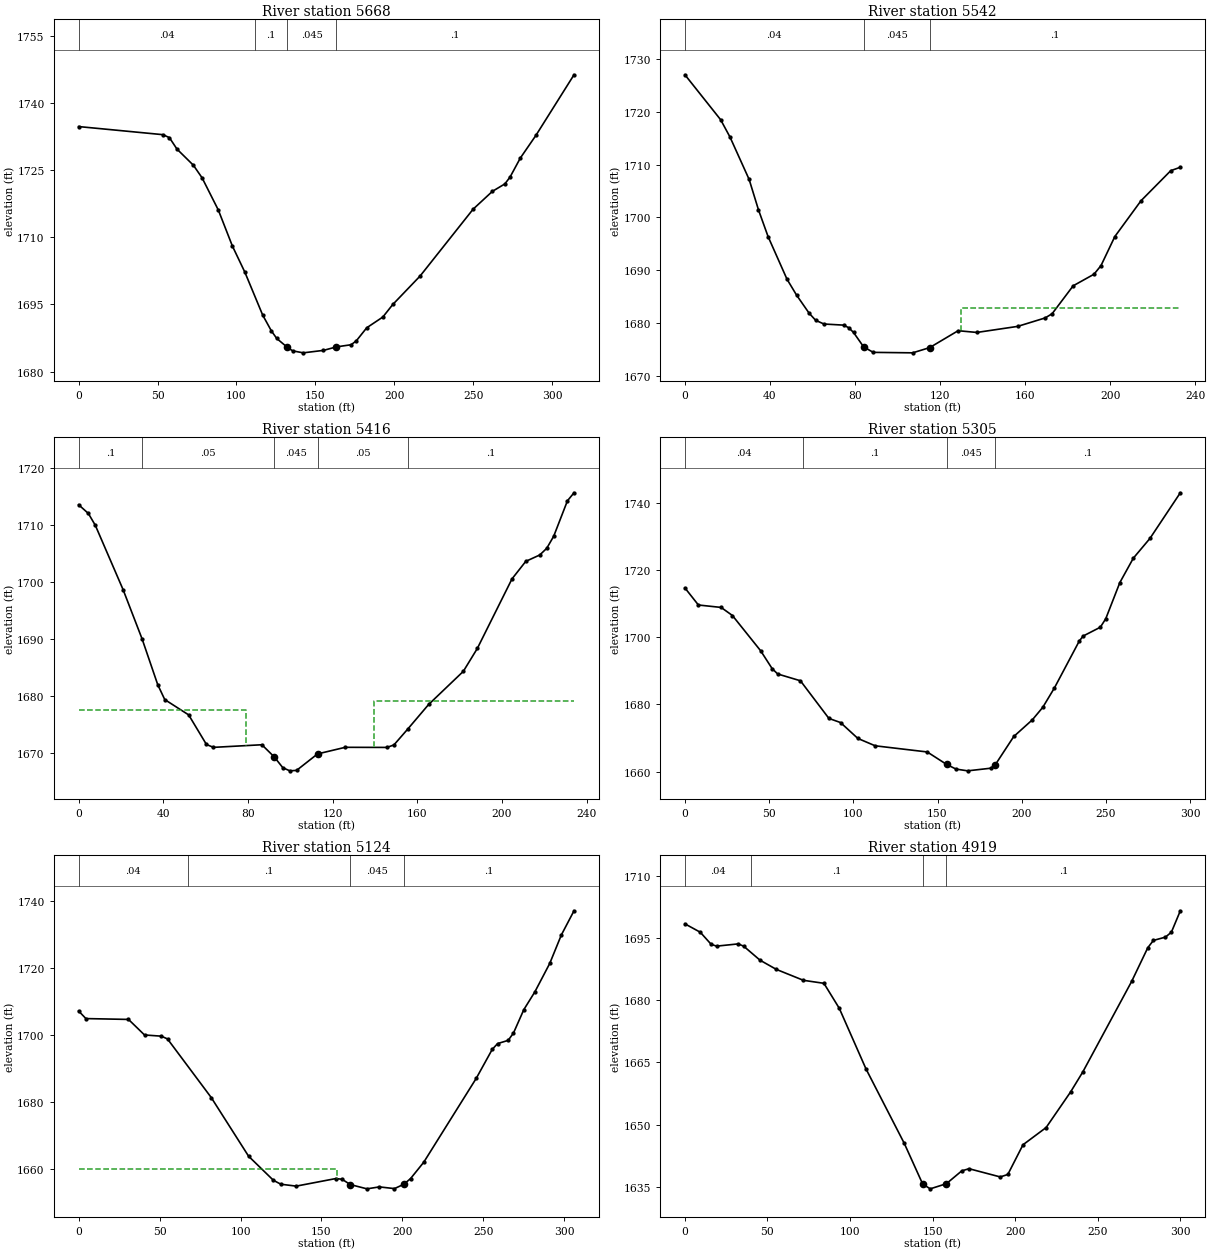
Type RM Length L Ch R = 1 ,5668    ,113.5,125.6,135.3
XS GIS Cut Line= 4
2006585.61180582259819.0201262262006548.91692255 259868.47824249
2006504.19809315260067.3769165652006501.26379612260115.668503453
#Sta/Elev= 30
       0 1734.74    53.4 1732.93    57.5 1732.27    62.3 1729.71    72.7  1726.1
    78.2 1723.29    88.5 1716.09    97.4 1708.05   105.3 1702.21   116.6 1692.62
   122.1 1689.09   125.5  1687.4   132.2 1685.42   135.6 1684.63   142.3 1684.19
   155.1 1684.74   163.3 1685.52   172.6    1686   175.9 1686.87   182.5 1689.79
   192.7 1692.19     199 1694.99   216.3 1701.35   249.9 1716.29   262.1 1720.27
     270 1721.93   273.3 1723.47   279.8 1727.71   289.7 1732.79   313.8 1746.31
#Mann= 4 ,-1 , 0
       0     .04       0  111.58      .1       0   132.2    .045       0
   163.3      .1       0
Bank Sta=132.2,163.3
XS Rating Curve= 0 ,0
Exp/Cntr=0.3,0.1

Type RM Length L Ch R = 1 ,5542    ,134,126.9,109.3
XS GIS Cut Line= 3
2006487.72977708259833.2199289852006379.71177837259949.996143806
2006378.73864324260023.954413193
#Sta/Elev= 30
       0 1727.08    16.8 1718.55    21.2 1715.26    30.2 1707.22    34.6 1701.44
    39.1 1696.38      48 1688.29    52.5 1685.27    58.4 1681.84    61.5 1680.48
    65.4 1679.78    74.6 1679.57      77 1679.09    79.3 1678.18    84.11675.413
    88.6  1674.4   107.1 1674.31   115.1  1675.3   128.5 1678.51   137.3 1678.18
   156.5 1679.33   169.4 1680.93   172.7 1681.73   182.6 1687.03   192.4 1689.23
   195.7 1690.87   202.2 1696.38   214.5 1703.17   228.5 1708.88     233 1709.53
#Mann= 3 ,-1 , 0
       0     .04       0    84.1    .045       0   115.1      .1       0
#XS Ineff= 2 , 0
                          129.77         1682.88
Permanent Ineff=
       F       F
Bank Sta=84.1,115.1
XS Rating Curve= 0 ,0
Exp/Cntr(USF)=0,0
Exp/Cntr=0.3,0.1

Type RM Length L Ch R = 1 ,5416    ,124.1,110.2,121.4
XS GIS Cut Line= 2
2006312.56545484259788.4557133032006318.89083315260022.494710508
#Sta/Elev= 30
       0 1713.53     4.6    1712     7.9 1709.91      21 1698.64      30 1689.97
    37.4 1681.93    40.7 1679.33      52 1676.64    60.4 1671.45    63.7 1670.94
    86.6  1671.4    92.4 1669.28    96.5 1667.37    99.8 1666.82     103  1666.9
   112.9 1669.79     126 1670.95   145.7 1670.93     149 1671.37   155.5 1674.14
   165.4 1678.47   181.8 1684.29   188.4  1688.3   204.8 1700.52   211.3 1703.59
   217.9 1704.71   221.2 1705.88   224.5    1708     231 1714.23   234.1 1715.63
#Mann= 5 ,-1 , 0
       0      .1       0      30     .05       0    92.4    .045       0
   112.9     .05       0   155.5      .1       0
#XS Ineff= 2 , 0
           78.97 1677.43  139.75         1679.07
Permanent Ineff=
       F       F
Bank Sta=92.4,112.9
XS Rating Curve= 0 ,0
Exp/Cntr(USF)=0,0
Exp/Cntr=0.3,0.1

Type RM Length L Ch R = 1 ,5305    ,157.7,181.6,193.3
XS GIS Cut Line= 4
2006201.10067252 259752.374302042006183.82742507259829.023223676
2006232.03180171259986.243652103 2006233.0412871260037.378740158
#Sta/Elev= 30
       0 1714.63       8 1709.56    21.5 1708.84    28.2 1706.44      45 1695.94
    51.8 1690.65    55.1 1689.06    68.6 1687.04    85.5 1675.86    92.4 1674.63
   102.7 1669.91     113 1667.72   143.9 1665.89   155.4 1662.19     161  1660.8
   167.9 1660.28   181.6 1661.06   184.3 1662.08   195.3 1670.49   206.3 1675.43
   212.5 1679.14   219.4 1684.89   234.2 1698.86   236.5 1700.34   246.7 1702.96
   249.9 1705.46   258.3 1716.24   266.3 1723.48   276.2 1729.37   294.2 1742.91
#Mann= 4 ,-1 , 0
       0     .04       0      70      .1       0   155.4    .045       0
   184.3      .1       0
Bank Sta=155.4,184.3
XS Rating Curve= 0 ,0
Exp/Cntr=0.3,0.1

Type RM Length L Ch R = 1 ,5124    ,224.4,204.6,182.5
XS GIS Cut Line= 4
2006117.71270149259749.1891439532006114.11648039 259796.39256872
2006027.34860243259938.0392754632006031.68060579260030.536744498
#Sta/Elev= 30
       0 1707.13     4.5 1704.86    30.8 1704.61    40.7 1699.96    51.1  1699.6
    54.9 1698.77    81.9 1681.25     105 1663.68   120.3 1656.49   124.9 1655.31
   134.4 1654.74   158.8    1657   162.7  1656.8   167.8 1655.21   178.1 1653.93
   185.8 1654.51   195.1    1654   200.8 1655.28     205 1656.98   213.2  1661.9
   245.6 1686.98   255.5 1695.66   258.8 1697.38   265.3 1698.34   268.6 1700.53
     275 1707.54   281.8 1712.84     291 1721.35   298.2  1729.9     306 1737.11
#Mann= 4 ,-1 , 0
       0     .04       0   67.34      .1       0   167.8    .045       0
   200.8      .1       0
#XS Ineff= 2 , 0
          159.52 1659.72
Permanent Ineff=
       F       F
Bank Sta=167.8,200.8
XS Rating Curve= 0 ,0
Exp/Cntr=0.3,0.1

Type RM Length L Ch R = 1 ,4919    ,142.6,145.5,153.4
XS GIS Cut Line= 4
2005801.69273309259773.900172925 2005808.0874785259857.857672522
2005902.01722317259953.6129971472005936.83605532260027.556354735
#Sta/Elev= 30
       0 1698.37     9.3 1696.35    15.9 1693.43    19.2    1693    32.3 1693.54
    35.6 1692.98    45.5 1689.61    55.4 1687.39    71.8 1684.76    84.2 1684.04
    93.5 1678.02   109.7  1663.4   132.9 1645.45     144 1635.69   148.6 1634.51
   158.4 1635.75   167.7 1638.84   172.1 1639.36     191 1637.38   195.6 1637.97
   204.8 1645.13   218.8 1649.28   233.6 1657.84     241 1662.66   270.6 1684.48
   280.4 1692.62   283.8 1694.38   291.1 1695.17   294.7 1696.37   300.1 1701.52
#Mann= 4 ,-1 , 0
       0     .04       0      40      .1       0     144    .045       0
   158.4      .1       0
Bank Sta=144,158.4
XS Rating Curve= 0 ,0
Exp/Cntr=0.3,0.1

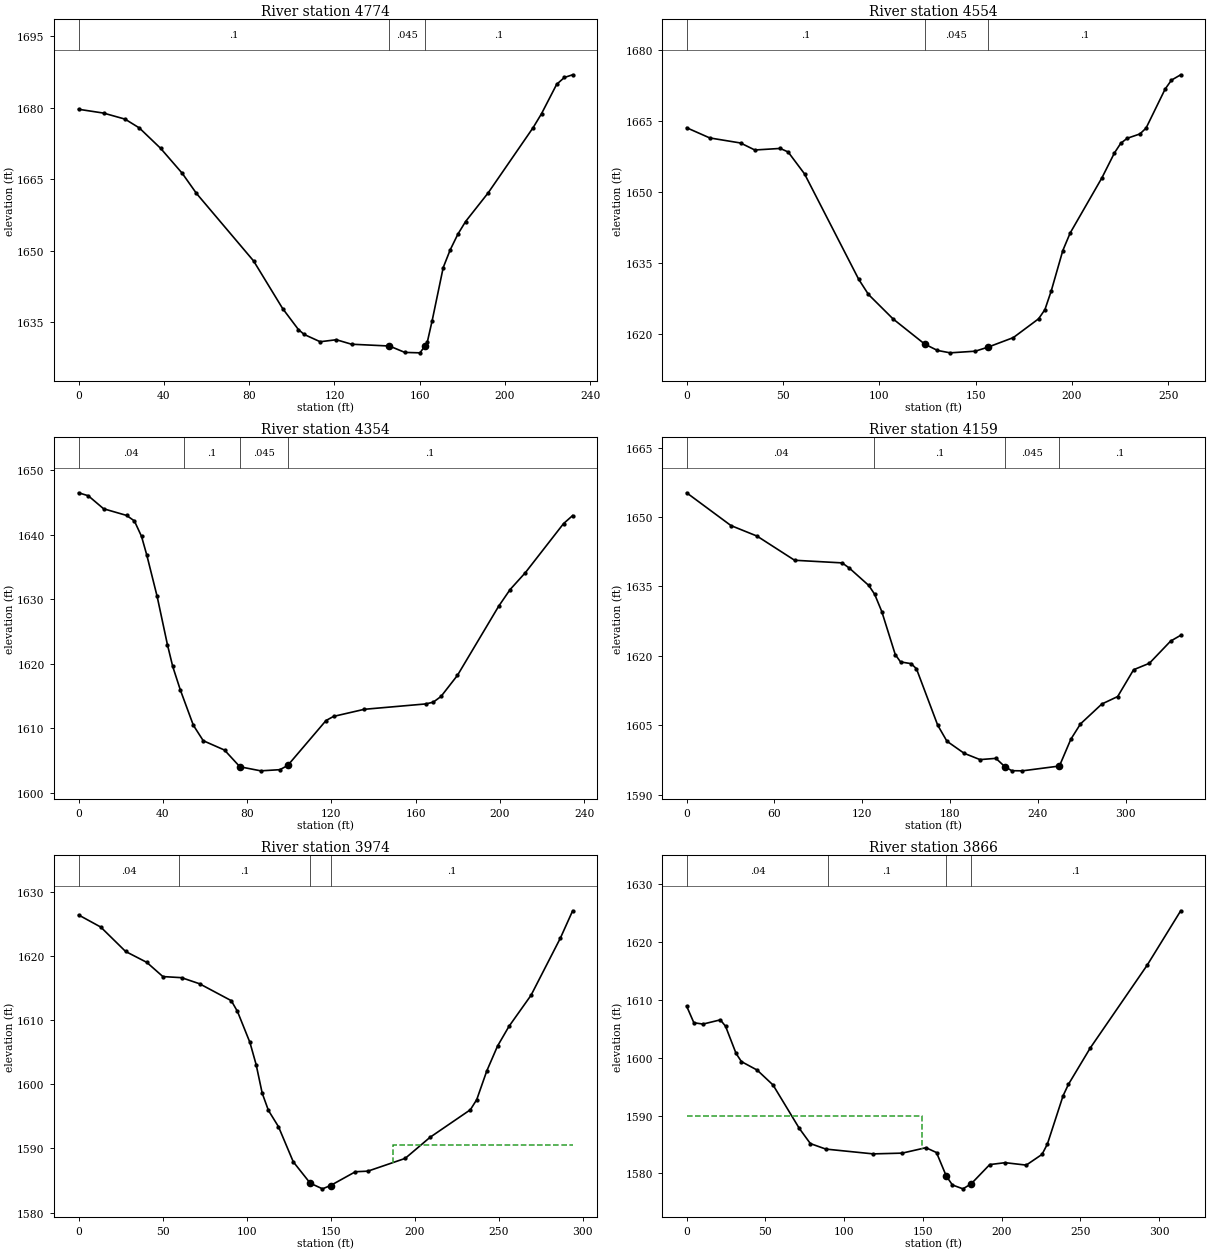
Type RM Length L Ch R = 1 ,4774    ,223.5,219.4,229.9
XS GIS Cut Line= 3
2005759.27071503259873.3949815712005741.83037156259958.804237708
2005798.07968786260091.926185844
#Sta/Elev= 30
       0 1679.67    11.7 1678.87    21.8  1677.6    28.5 1675.75    38.5 1671.46
    48.6 1666.24    55.3    1662    82.1 1647.82    95.7 1637.84   103.1 1633.43
   105.8  1632.4   113.3 1630.87   120.9 1631.29     128 1630.35   145.8 1629.97
     153 1628.63   160.1 1628.54   162.6 1630.07   163.6 1630.91   165.8 1635.26
     171 1646.44   174.3 1650.18   177.9 1653.47   181.5 1656.11   192.1 1662.13
   213.2 1675.84   217.1 1678.74   224.2  1684.9   227.8 1686.34   231.7 1686.91
#Mann= 3 ,-1 , 0
       0      .1       0   145.8    .045       0   162.6      .1       0
Bank Sta=145.8,162.6
XS Rating Curve= 0 ,0
Exp/Cntr=0.3,0.1

Type RM Length L Ch R = 1 ,4554    ,178.2,200.7,200
XS GIS Cut Line= 3
2005635.99381587259860.8189559182005560.87855772259918.015919012
2005555.33653761260080.032312112
#Sta/Elev= 30
       0 1663.54      12 1661.38      28 1660.31    35.4 1658.83    48.6 1659.16
    52.7 1658.41    61.2 1653.79    89.3 1631.52    94.4 1628.29   107.2 1623.11
   123.6  1617.8   130.2 1616.46   136.8 1615.95   149.9  1616.3   156.5 1617.16
   169.6 1619.17   182.7 1623.14     186 1625.08   189.3 1629.06   195.3 1637.58
   199.1 1641.27   215.6 1652.95   222.1 1658.21   225.4 1660.26   228.7  1661.3
   235.3 1662.22   238.5 1663.45   248.4  1671.7   251.7  1673.6   256.5 1674.73
#Mann= 3 ,-1 , 0
       0      .1       0   123.6    .045       0   156.5      .1       0
Bank Sta=123.6,156.5
XS Rating Curve= 0 ,0
Exp/Cntr=0.3,0.1

Type RM Length L Ch R = 1 ,4354    ,193,194.1,197.2
XS GIS Cut Line= 2
2005452.61671902259769.1697032172005350.97816168259980.556277265
#Sta/Elev= 30
       0  1646.5     4.6 1646.04    11.9 1644.02    22.8 1642.99    26.5 1642.14
    29.9 1639.74    32.4 1636.84    37.3 1630.45    42.2 1622.95    44.7 1619.59
    48.3 1615.96    54.5 1610.47    59.2 1608.07    69.3 1606.62    76.6 1604.03
    86.5  1603.4    95.6 1603.58    99.3 1604.23   117.5  1611.2   121.1 1611.84
   135.7 1612.94   164.8 1613.77   168.4 1614.04   172.1 1614.93   179.9  1618.2
   199.5 1628.93   204.9  1631.5   212.1  1634.1   230.3 1641.73   234.6 1642.97
#Mann= 4 ,-1 , 0
       0     .04       0      50      .1       0    76.6    .045       0
    99.3      .1       0
Bank Sta=76.6,99.3
XS Rating Curve= 0 ,0
Exp/Cntr=0.3,0.1

Type RM Length L Ch R = 1 ,4159    ,184.1,185.2,189
XS GIS Cut Line= 3
 2005352.8994775259634.7809252842005299.17065676259657.619533361
2005181.22014569259910.814926748
#Sta/Elev= 30
       0 1655.25    30.3 1648.16    48.1 1645.89    73.8 1640.66   106.3 1640.09
   111.2 1638.97   124.5 1635.21   128.5 1633.32   133.4 1629.56   142.6 1620.27
   146.2 1618.68   153.5  1618.3   157.1 1617.19   171.6 1605.01   177.9 1601.54
   189.7 1598.92   200.5 1597.56   211.4 1597.83   217.4 1596.06   222.2 1595.16
   229.5 1595.13   254.8 1596.17   262.6 1601.96   269.2 1605.28   283.8 1609.58
   294.6 1611.19   305.5 1616.99   316.3 1618.39   330.8 1623.18   337.7 1624.44
#Mann= 4 ,-1 , 0
       0     .04       0  128.38      .1       0   217.4    .045       0
   254.8      .1       0
Bank Sta=217.4,254.8
XS Rating Curve= 0 ,0
Exp/Cntr=0.3,0.1

Type RM Length L Ch R = 1 ,3974    ,112.3,108.3,106.9
XS GIS Cut Line= 3
2005135.06391945259590.9935550542005034.53513398259784.635068054
2005030.41510179259860.443660377
#Sta/Elev= 30
       0 1626.45    13.2 1624.56      28 1620.75    40.6 1619.05    50.2 1616.83
    61.3 1616.66      72 1615.71    90.9 1613.07    94.6 1611.38     102 1606.55
   105.7 1603.09   109.3 1598.64     113 1595.95     119  1593.4   127.8 1587.92
   137.9 1584.58   145.2  1583.7     150 1584.22   164.8 1586.37   172.2 1586.46
   194.4 1588.45   209.2 1591.74   233.2 1596.04     237 1597.62     243 1602.11
   249.4 1605.99   256.2 1609.06   269.3  1613.9   286.8 1622.84   294.1  1627.1
#Mann= 4 ,-1 , 0
       0     .04       0      60      .1       0   137.9    .045       0
     150      .1       0
#XS Ineff= 2 , 0
                           187.1         1590.62
Permanent Ineff=
       F       F
Bank Sta=137.9,150
XS Rating Curve= 0 ,0
Exp/Cntr=0.3,0.1

Type RM Length L Ch R = 1 ,3866    ,128.5,126.4,123.9
XS GIS Cut Line= 2
2004996.65501034259535.8589022762004933.28695479259843.150568932
#Sta/Elev= 30
       0 1608.91     4.6 1606.03    10.4  1605.8    21.4 1606.53    24.7 1605.44
    31.4 1600.73    34.8 1599.32    44.8 1597.85    54.9 1595.27    71.6 1587.76
    78.6 1585.15    88.4  1584.2   118.5 1583.37   136.9  1583.5     152 1584.44
   158.7  1583.6   164.91579.547   168.8    1578   175.5 1577.33   180.71578.188
   192.5 1581.52   202.3 1581.85   215.7 1581.43   225.7 1583.28   229.1 1585.05
   239.1 1593.42   242.5 1595.39   256.3 1601.65   292.5 1615.98   313.8 1625.38
#Mann= 4 ,-1 , 0
       0     .04       0      90      .1       0   164.9    .045       0
   180.7      .1       0
#XS Ineff= 2 , 0
          149.69 1589.96
Permanent Ineff=
       F       F
Bank Sta=164.9,180.7
XS Rating Curve= 0 ,0
Exp/Cntr(USF)=0,0
Exp/Cntr=0.3,0.1

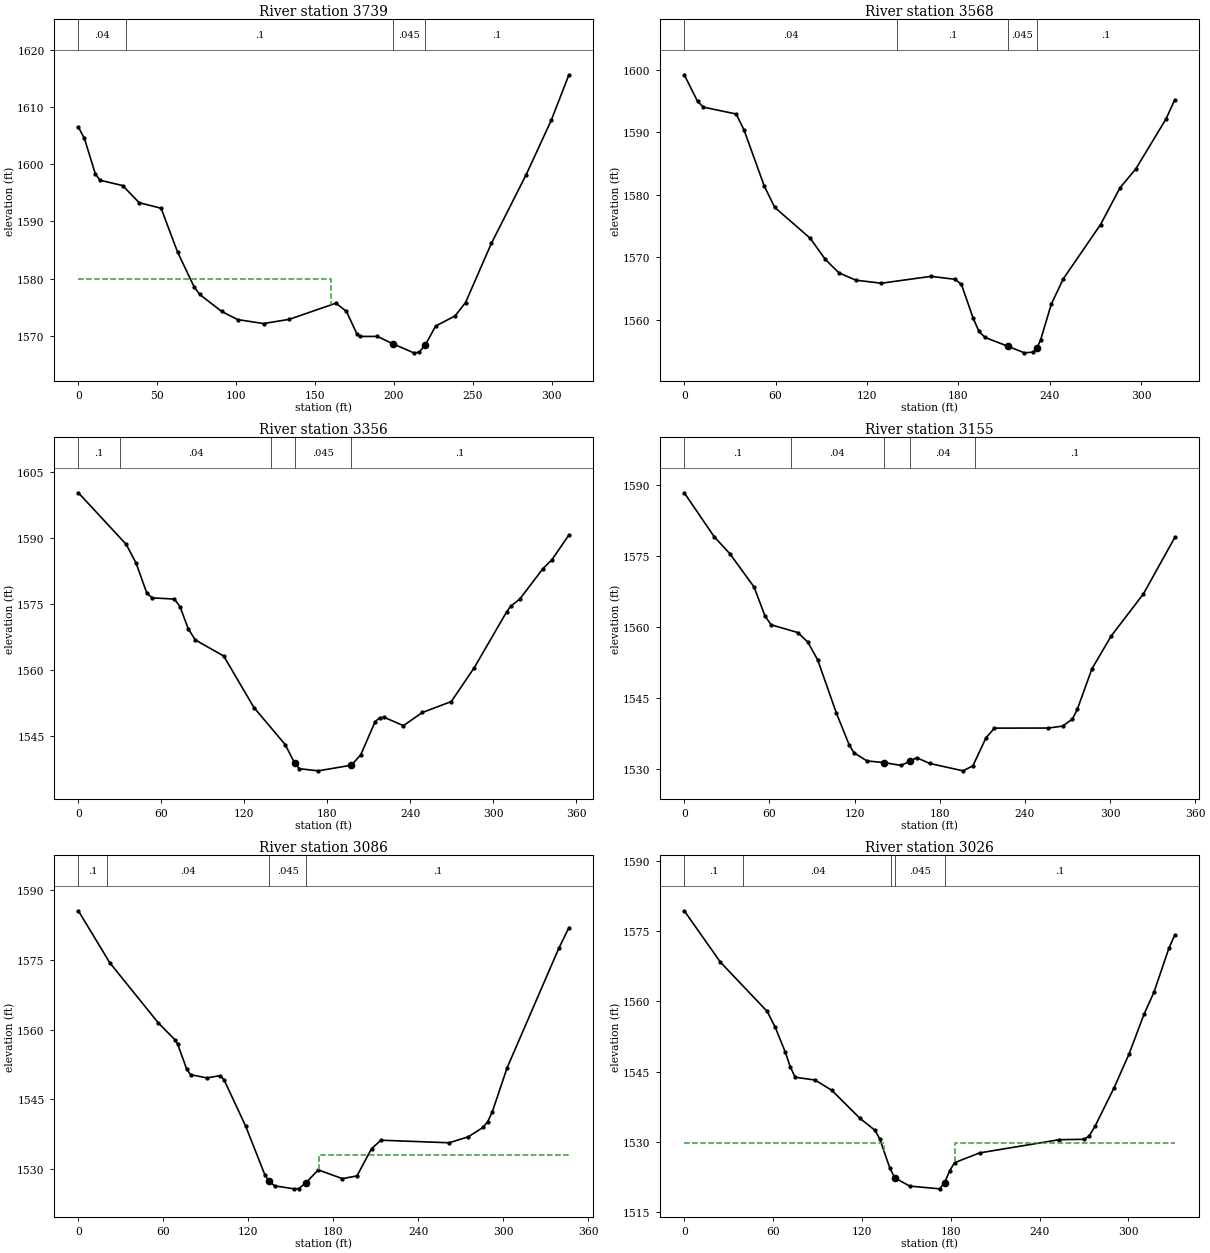
Type RM Length L Ch R = 1 ,3739    ,159.4,171.8,185.9
XS GIS Cut Line= 3
2004872.83838192259494.1846224512004840.71989699259586.080156583
2004834.30156948259799.467183943
#Sta/Elev= 30
       0  1606.5     3.8 1604.54    10.7 1598.35    13.6 1597.22    28.1 1596.27
    38.5 1593.28    52.4 1592.31    62.9  1584.6    73.3 1578.58    76.8 1577.24
    90.8 1574.25   100.9 1572.83   117.3 1572.13   133.7 1572.88   163.2  1575.7
   169.8 1574.27   176.4 1570.36   178.5 1569.88   189.5 1569.88   199.4 1568.57
   212.5 1567.01   215.8  1567.1   219.9 1568.43   226.3 1571.68   238.7 1573.48
   245.3 1575.81   261.7 1586.18   283.7 1598.18   299.6  1607.7   310.8 1615.66
#Mann= 4 ,-1 , 0
       0     .04       0      30      .1       0   199.4    .045       0
   219.9      .1       0
#XS Ineff= 2 , 0
             160    1580
Permanent Ineff=
       F       F
Bank Sta=199.4,219.9
XS Rating Curve= 0 ,0
Exp/Cntr=0.3,0.1

Type RM Length L Ch R = 1 ,3568    ,230.1,211.6,168.3
XS GIS Cut Line= 4
2004755.19286686259485.3666546422004725.98543137259643.055819728
2004641.48406291259699.7624049092004634.95960314259759.515165086
#Sta/Elev= 30
       0 1599.22     8.7 1594.98    12.6 1594.04    34.1 1592.94    39.3 1590.36
    52.6 1581.38    59.4 1578.01    82.7 1573.06    92.7 1569.66   101.6 1567.52
   112.7 1566.35   129.4 1565.86     162 1566.96   177.8 1566.49     182  1565.7
   189.7  1560.3   193.6 1558.14   197.6 1557.18   212.7 1555.76   223.4 1554.72
   229.2 1554.84   231.6 1555.51     234 1556.74   241.1 1562.53     249 1566.58
   273.4 1575.24   286.2 1581.13   296.6 1584.16   316.4 1592.14   322.2 1595.23
#Mann= 4 ,-1 , 0
       0     .04       0     140      .1       0   212.7    .045       0
   231.6      .1       0
Bank Sta=212.7,231.6
XS Rating Curve= 0 ,0
Exp/Cntr=0.3,0.1

Type RM Length L Ch R = 1 ,3356    ,183.9,201.1,228.8
XS GIS Cut Line= 4
2004567.77649137259401.050899297 2004522.8271358259466.568582871
2004580.05926397259660.5527210892004571.12743574259733.096126456
#Sta/Elev= 30
       0  1600.2    34.6 1588.51    41.7  1584.3    49.6 1577.39    53.5  1576.4
    69.5 1576.12    73.5 1574.41    79.5 1569.37    84.6 1566.86   105.1 1563.23
     127 1551.55   149.6 1543.16   156.4 1538.98   159.9  1537.7   173.5 1537.22
   197.5  1538.5   204.3 1540.89   214.6 1548.35     218 1549.27   221.4 1549.31
   235.1 1547.46   248.8 1550.44   269.7 1552.91   286.3 1560.57   309.7  1573.2
   312.7 1574.51   319.3 1576.14   335.8 1582.94   342.5 1585.04   354.8 1590.63
#Mann= 5 ,-1 , 0
       0      .1       0      30     .04       0  139.45      .1       0
   156.4    .045       0   197.5      .1       0
Bank Sta=156.4,197.5
XS Rating Curve= 0 ,0
Exp/Cntr=0.3,0.1

Type RM Length L Ch R = 1 ,3155    ,76,69.2,62.7
XS GIS Cut Line= 4
 2004462.3961606 259352.824950362004443.39328806259404.569042189
2004330.46155768259537.3238954562004298.61203662259649.156042705
#Sta/Elev= 30
       0 1588.33    21.1 1579.05    32.1 1575.47    49.2 1568.43    56.9 1562.31
    61.2 1560.45      80 1558.81      87 1556.82      94 1553.06   107.2  1541.8
   116.2 1535.11   119.6 1533.41   128.9 1531.68   140.5 1531.36   152.8 1530.74
   159.1 1531.64   163.8 1532.38     173 1531.16   196.4  1529.6   203.4 1530.66
   212.7  1536.6   218.6 1538.62   256.5 1538.64   266.7 1539.05   273.6 1540.56
     277 1542.61   287.3 1551.15   300.8 1558.05   323.6 1566.98   345.7  1578.9
#Mann= 5 ,-1 , 0
       0      .1       0   75.12     .04       0   140.5    .045       0
   159.1     .04       0  205.12      .1       0
Bank Sta=140.5,159.1
XS Rating Curve= 0 ,0
Exp/Cntr=0.5,0.3

Type RM Length L Ch R = 1 ,3086    ,60.9,60.2,60.3
XS GIS Cut Line= 2
2004365.44190609259302.5913016512004266.56113349259634.665896284
#Sta/Elev= 30
       0 1585.58    22.2 1574.38    56.4 1561.46    68.1 1557.83    70.1 1556.88
    76.5 1551.49    79.2 1550.31    90.7 1549.59   100.3 1550.09   102.9 1549.18
   118.1 1539.25   131.7 1528.74   134.6 1527.38   138.6 1526.36   152.3 1525.71
   155.7 1525.78   160.9 1527.05   169.4 1529.79   186.5 1527.91   196.8  1528.5
   207.1 1534.37   213.7 1536.18   261.8 1535.63   275.5 1536.92   285.8 1538.94
   289.2  1540.2   292.3 1542.23   302.9 1551.82   339.4 1577.53   346.5 1581.96
#Mann= 4 ,-1 , 0
       0      .1       0      20     .04       0   134.6    .045       0
   160.9      .1       0
#XS Ineff= 2 ,-1
       0     120  1532.9     170346.4837  1532.9
Permanent Ineff=
       F       F
Bank Sta=134.6,160.9
XS Rating Curve= 0 ,0
Exp/Cntr(USF)=0,0
Exp/Cntr=0.5,0.3

Type RM Length L Ch R = 1 ,3026    ,65.4,67.1,61.5
XS GIS Cut Line= 2
2004298.69738458259286.9351793232004224.53680514259609.945703135
#Sta/Elev= 30
       0 1579.41    24.4 1568.42      56 1557.87    61.5 1554.45    68.2 1549.19
    71.6 1546.02    74.9 1543.78    88.4 1543.17    99.8 1540.94   118.7 1534.97
   128.8 1532.42   132.1 1530.55   138.9 1524.32   142.2 1522.23   152.3 1520.47
   172.5 1519.88   175.9  1521.2   179.3 1523.75   182.6 1525.48   199.5 1527.57
   253.3  1530.4   270.2 1530.49   273.5 1531.17   277.7  1533.4   290.4 1541.53
   300.5 1548.76   310.6 1557.25   317.3 1561.96   327.4 1571.38   331.4 1574.24
#Mann= 5 ,-1 , 0
       0      .1       0      40     .04       0     140      .1       0
   142.2    .045       0   175.9      .1       0
#XS Ineff= 2 , 0
           134.9  1529.8   183.2          1529.8
Permanent Ineff=
       F       F
Bank Sta=142.2,175.9
XS Rating Curve= 0 ,0
Exp/Cntr(USF)=0,0
Exp/Cntr=0.5,0.3