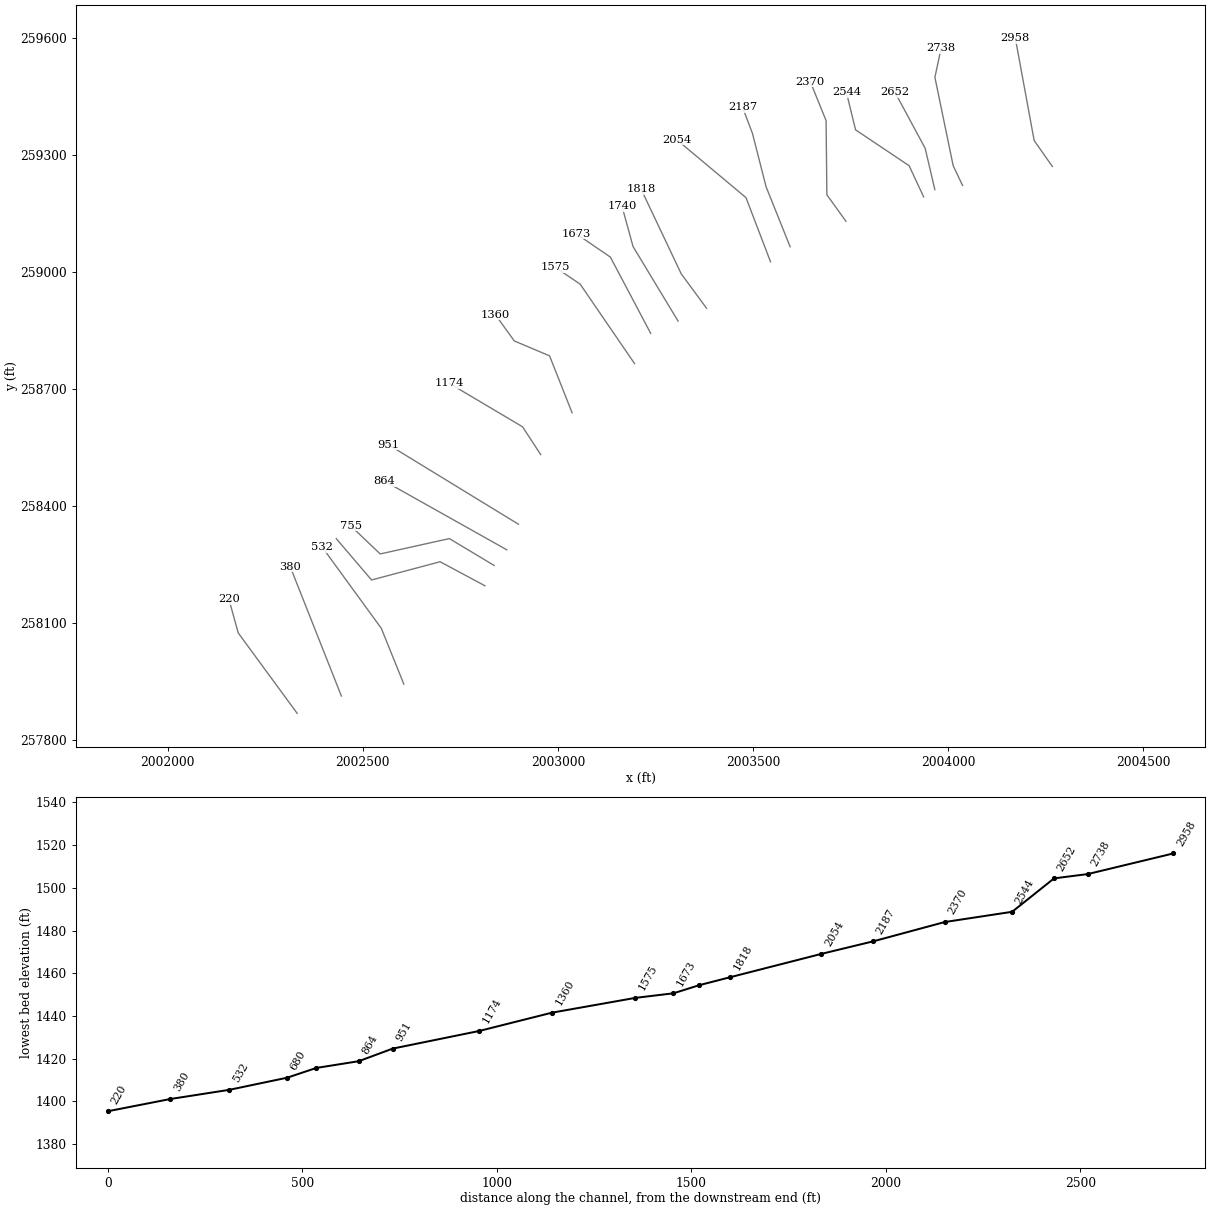
HEC-RAS study BRKSBR_A.prj: BRKSBR_A

--- BRKSBR_A.g01 (geometry) --- (continued)

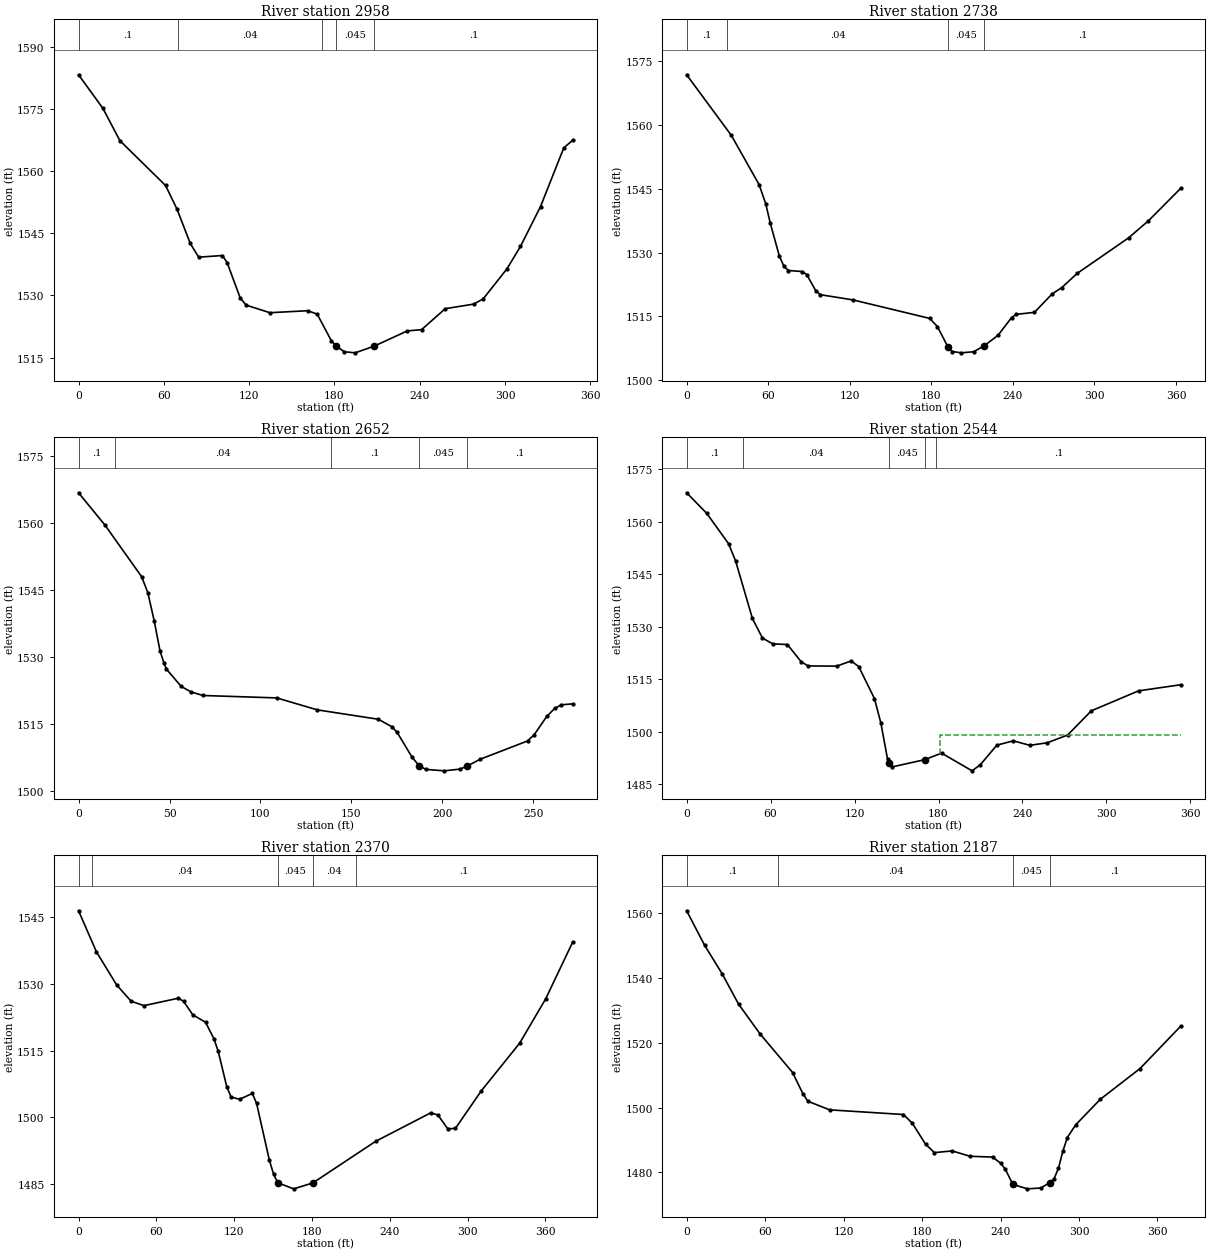
Type RM Length L Ch R = 1 ,2958    ,219.8,220.2,220.6
XS GIS Cut Line= 3
2004267.74355895259270.519175326 2004221.0895077259337.055792367
2004172.83665048259598.942668509
#Sta/Elev= 30
       0 1583.33    17.1 1575.23    29.1  1567.4    61.2 1556.58    69.2 1550.92
    78.6 1542.56    84.5 1539.25   101.2 1539.65   104.6 1537.88   113.7 1529.42
   117.9 1527.66   134.6 1525.83   161.3 1526.31   167.9 1525.48   177.9 1519.02
   181.3 1517.78   181.3 1517.77   186.9  1516.4   194.6 1516.13     208 1517.75
   231.3 1521.43   241.3 1521.73     258  1526.8     278 1527.91   284.7 1529.18
   301.4 1536.43   310.9 1541.84     325 1551.47   341.4 1565.69   347.6 1567.49
#Mann= 5 ,-1 , 0
       0      .1       0      70     .04       0  171.26      .1       0
   181.3    .045       0     208      .1       0
Bank Sta=181.3,208
XS Rating Curve= 0 ,0
Exp/Cntr=0.3,0.1

Type RM Length L Ch R = 1 ,2738    ,82.6,86.7,93
XS GIS Cut Line= 4
2004037.53745991259221.9523309412004013.45606395259272.573077535
2003966.60140986259499.0372389912003982.50368877259573.506117045
#Sta/Elev= 30
       0 1571.83    32.9 1557.57    53.3 1546.01    58.2 1541.49    61.5 1536.97
    68.2 1529.21    71.6 1526.79    74.9 1525.81      85 1525.57    88.3 1524.86
      95 1521.06    98.4 1520.12   122.3  1518.9   178.8 1514.55   184.5 1512.63
   192.2 1507.85   195.5 1506.76   202.2 1506.45   211.2 1506.71     219 1508.12
   229.1 1510.58   239.1 1514.75   242.5  1515.5   255.9 1515.97   268.9 1520.31
     276 1521.79   287.3 1525.12   325.1 1533.47   339.7 1537.48   363.5 1545.13
#Mann= 4 ,-1 , 0
       0      .1       0      30     .04       0   192.2    .045       0
     219      .1       0
Bank Sta=192.2,219
XS Rating Curve= 0 ,0
Exp/Cntr=0.3,0.1

Type RM Length L Ch R = 1 ,2652    ,101,107.7,117.6
XS GIS Cut Line= 3
2003966.49043125259211.3245130622003941.62142254  259317.2881154
2003864.31124328259460.555230806
#Sta/Elev= 30
       0  1566.8    14.5 1559.56    34.7 1547.97    38.1 1544.36    41.6 1538.05
    44.8 1531.29      47 1528.55    48.2  1527.3    56.4 1523.38    61.7 1522.15
    68.4 1521.33   108.9 1520.79   131.2 1518.11   164.8    1516   172.2 1514.33
   175.1 1513.08   183.4 1507.44   187.2  1505.6   187.2 1505.59   190.9 1504.76
     201 1504.43   209.5 1504.81   213.3 1505.42   220.7 1507.02   246.8 1511.13
   250.5 1512.54   257.4 1516.64   261.7 1518.42   265.4 1519.24   271.6 1519.46
#Mann= 5 ,-1 , 0
       0      .1       0      20     .04       0  138.84      .1       0
   187.2    .045       0   213.3      .1       0
Bank Sta=187.2,213.3
XS Rating Curve= 0 ,0
Exp/Cntr(USF)=0,0
Exp/Cntr=0.3,0.1

Type RM Length L Ch R = 1 ,2544    ,183.9,173.5,147.9
XS GIS Cut Line= 4
2003937.76777657259192.6798852972003900.52433357259272.573077535
2003763.28179389259364.4269464662003739.52877005259461.374388611
#Sta/Elev= 30
       0 1568.29    14.4 1562.39      30  1553.7      35 1548.78      47 1532.35
    54.2 1526.73    61.5 1525.09      72 1524.89    81.9 1519.95    86.8 1518.78
   107.2 1518.71   117.6  1520.2     123 1518.57   134.2 1509.45   138.8 1502.47
   143.6 1492.05   144.5 1491.06   146.6 1489.87   170.3 1491.98   182.2 1493.84
     204 1488.77   209.9 1490.52   221.7 1496.12   233.5 1497.35   245.3 1496.06
   257.7  1496.8   272.3 1499.01   289.2 1505.93     323 1511.65   353.1 1513.39
#Mann= 5 ,-1 , 0
       0      .1       0      40     .04       0   144.5    .045       0
   170.3     .04       0  178.15      .1       0
#XS Ineff= 2 , 0
                           181.1         1499.16
Permanent Ineff=
       F       F
Bank Sta=144.5,170.3
XS Rating Curve= 0 ,0
Exp/Cntr=0.3,0.1

Type RM Length L Ch R = 1 ,2370    ,180.6,183.4,189.8
XS GIS Cut Line= 4
2003738.57492566  259130.19369962003689.67839015259198.086191539
2003687.65580971259388.1412199792003647.32912289259487.486933689
#Sta/Elev= 30
       0  1546.4    13.8 1537.17    29.4 1529.73    40.6 1526.08    50.5  1525.1
      77 1526.77      81 1526.05    88.1 1523.04    97.9 1521.37   104.5  1517.6
   107.7 1514.83   114.3 1506.89   117.6 1504.58   124.2 1504.07     134 1505.38
   137.3 1503.14   147.1 1490.46   150.4 1487.22   153.7 1485.31   165.9 1483.96
   180.7 1485.29   229.1 1494.63   271.6 1501.03   277.1 1500.55   284.7 1497.45
   290.6 1497.53   310.6 1505.97   340.1 1516.65   360.2 1526.61     381 1539.34
#Mann= 5 ,-1 , 0
       0      .1       0      10     .04       0   153.7    .045       0
   180.7     .04       0  213.67      .1       0
Bank Sta=153.7,180.7
XS Rating Curve= 0 ,0
Exp/Cntr=0.3,0.1

Type RM Length L Ch R = 1 ,2187    ,125.2,133.2,145.5
XS GIS Cut Line= 4
2003595.47652233259064.9851337152003533.80841441 259218.71630715
2003499.01158389259355.0304964412003473.65892184259421.910521671
#Sta/Elev= 30
       0 1560.65    13.8 1549.97    27.1 1541.27    39.7 1531.88    56.2 1522.67
      81  1510.8    88.9 1504.25    92.7 1501.94   109.3 1499.29   165.8 1497.85
   172.6 1495.15   182.7 1488.68   189.5 1486.11   203.1 1486.63   216.6 1484.98
   233.9 1484.73   240.3 1482.79   243.7 1480.94   249.5 1476.29   260.6 1474.94
   270.8  1475.2   277.6 1476.84   280.9 1478.03   284.3 1481.27   287.7 1486.57
   291.1 1490.76   297.5 1494.68   316.3 1502.54   346.7 1512.02   377.8 1525.08
#Mann= 4 ,-1 , 0
       0      .1       0      70     .04       0   249.5    .045       0
   277.6      .1       0
Bank Sta=249.5,277.6
XS Rating Curve= 0 ,0
Exp/Cntr=0.3,0.1

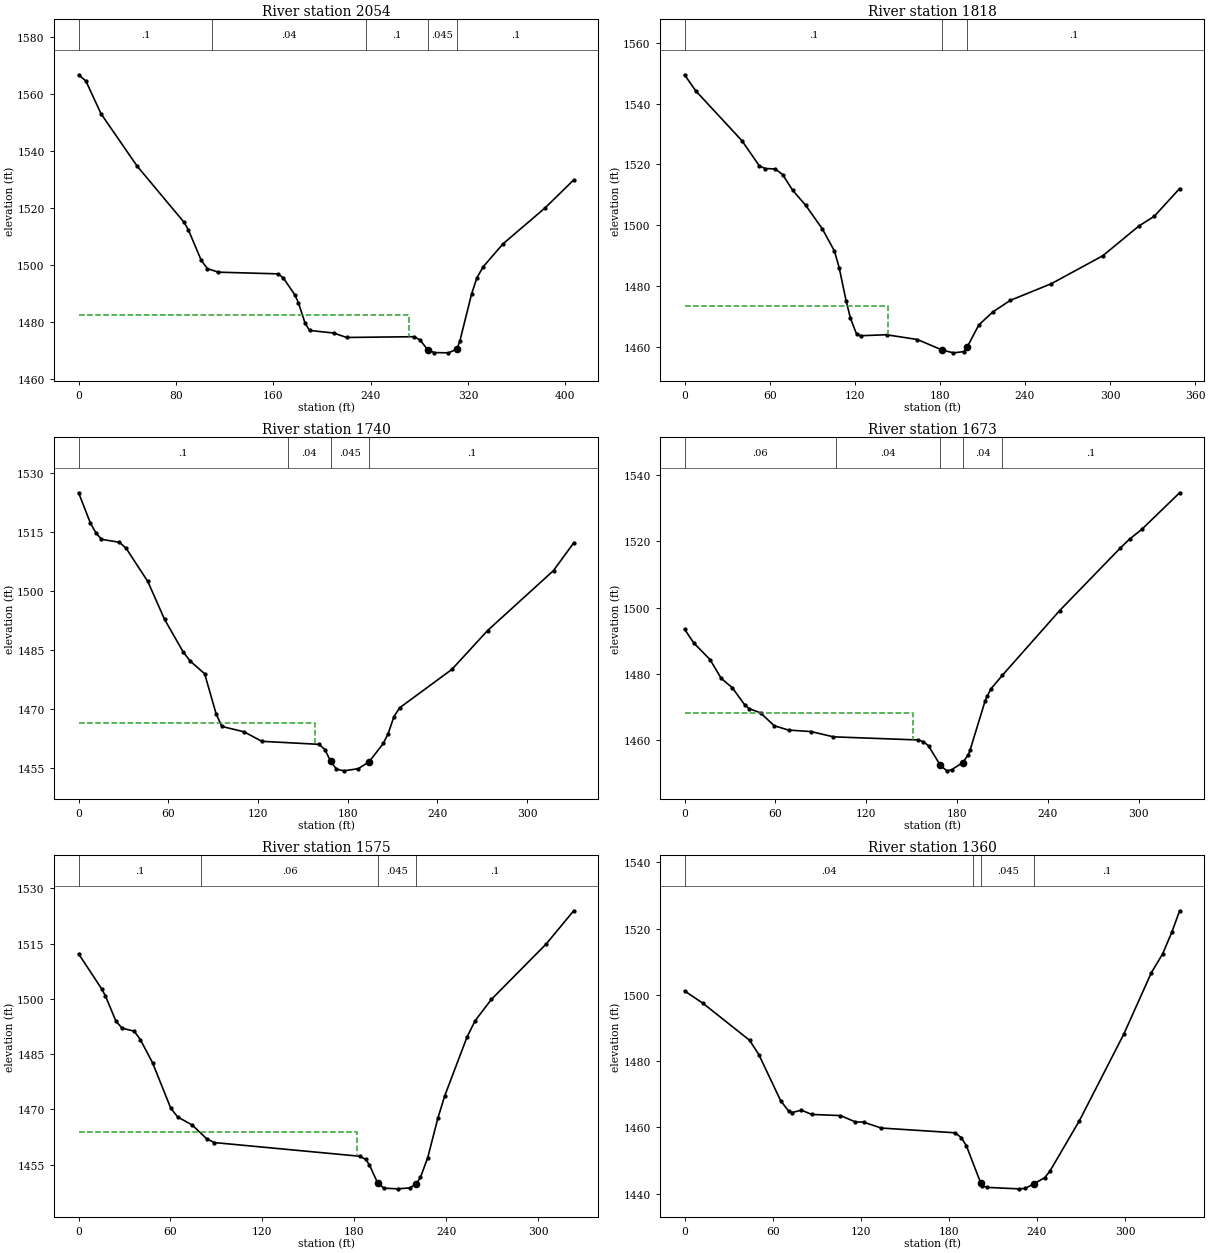
Type RM Length L Ch R = 1 ,2054    ,243.3,235.8,233.3
XS GIS Cut Line= 3
2003545.26612142259026.3102911562003482.34410778259190.791614011
2003305.28544316259338.858216614
#Sta/Elev= 30
       0 1566.58       6 1564.39    18.4 1552.93    48.1 1534.55    86.8 1514.78
    90.3 1512.11   100.8  1501.5   105.9 1498.59   114.9 1497.35     164 1496.76
   168.3 1495.31   177.6 1489.48   180.6  1486.7   186.2 1479.37   189.9 1476.91
   209.7 1476.01   220.2 1474.45     276 1474.72   280.7 1473.52     2871470.089
   292.4 1469.15     304 1469.06     311  1470.4   313.3 1473.12     323 1489.71
   327.3 1495.32   332.4 1499.18   348.7 1507.24   383.6 1519.97   406.9  1529.7
#Mann= 5 ,-1 , 0
       0      .1       0     110     .04       0  236.11      .1       0
     287    .045       0     311      .1       0
#XS Ineff= 2 , 0
          271.96 1482.48
Permanent Ineff=
       F       F
Bank Sta=287,311
XS Rating Curve= 0 ,0
Exp/Cntr(USF)=0,0
Exp/Cntr=0.3,0.1

Type RM Length L Ch R = 1 ,1818    ,76.5,78.3,79.6
XS GIS Cut Line= 3
2003381.20362145258907.3866800672003316.09945479258995.928346723
2003213.66889924259212.074180067
#Sta/Elev= 30
       0 1549.48     7.9 1544.19    40.5 1527.79    52.7 1519.55    56.8 1518.66
    63.9 1518.52    69.2 1516.67    76.2 1511.52    85.3 1506.64    97.1 1498.86
   105.7 1491.52   109.1 1485.91   113.9  1475.2     117 1469.42   121.3 1464.23
   124.3 1463.69   142.4 1464.01   164.2 1462.44   181.7 1458.97   189.6 1458.06
   196.9 1458.46   199.4 1460.05   207.5 1467.25   217.4 1471.52   229.7 1475.31
   258.6 1480.79   294.9 1489.97   320.3 1499.73   331.2 1502.95   349.1 1512.07
#Mann= 3 ,-1 , 0
       0      .1       0   181.7    .045       0   199.4      .1       0
#XS Ineff= 2 , 0
          143.79 1473.35
Permanent Ineff=
       F       F
Bank Sta=181.7,199.4
XS Rating Curve= 0 ,0
Exp/Cntr(USF)=0,0
Exp/Cntr=0.3,0.1

Type RM Length L Ch R = 1 ,1740    ,67.7,66.5,65.6
XS GIS Cut Line= 3
2003308.28695479258874.4005689472003192.83556589259065.372791156
2003164.18973255259169.539457828
#Sta/Elev= 30
       0 1524.94     7.9 1517.24    11.5 1514.83    15.3 1513.13    27.3 1512.38
    31.8 1510.85    46.3 1502.43    57.5 1492.82      70 1484.53    74.8 1482.18
    84.3 1479.03      92 1468.86    95.8 1465.66   110.6  1464.3   122.6 1461.88
     161 1461.11   164.8 1459.75   168.7 1456.76   172.5 1454.83   177.5 1454.39
   187.1 1454.94   194.3 1456.67   203.8 1461.33     207 1463.76     211 1468.16
   214.7 1470.37   249.7 1480.12   273.6 1489.99   317.7  1505.2   331.2 1512.22
#Mann= 4 ,-1 , 0
       0      .1       0     140     .04       0   168.7    .045       0
   194.3      .1       0
#XS Ineff= 2 , 0
          158.07 1466.51
Permanent Ineff=
       F       F
Bank Sta=168.7,194.3
XS Rating Curve= 0 ,0
Exp/Cntr(USF)=0,0
Exp/Cntr=0.3,0.1

Type RM Length L Ch R = 1 ,1673    ,97.6,97.8,99.5
XS GIS Cut Line= 3
2003237.97445479258843.1505689322003134.67584369259038.463068932
2003047.00223258259098.358902276
#Sta/Elev= 30
       0 1493.44     6.1 1489.27    16.8 1484.27    24.2 1478.58    31.6  1475.7
    39.8 1470.51    42.8 1469.37    50.2 1468.13    59.2 1464.22    68.7 1462.91
    83.5 1462.46    98.4 1460.86   154.1 1459.92   157.8 1459.42   161.2 1458.12
     169 1452.23   173.3 1450.57   176.4 1450.89   183.8 1453.06   187.5 1455.47
   188.6 1456.78   198.6 1471.77     200 1473.21   202.4 1475.37     210  1479.5
   247.8 1499.07   287.9 1518.01     294 1520.71     302 1523.63   327.1 1534.74
#Mann= 5 ,-1 , 0
       0     .06       0     100     .04       0     169    .045       0
   183.8     .04       0     210      .1       0
#XS Ineff= 2 , 0
          150.62 1468.21
Permanent Ineff=
       F       F
Bank Sta=169,183.8
XS Rating Curve= 0 ,0
Exp/Cntr(USF)=0,0
Exp/Cntr=0.3,0.1

Type RM Length L Ch R = 1 ,1575    ,197.3,214.9,223.9
XS GIS Cut Line= 3
2003196.61542202258765.6825002462003057.24643184258969.140880072
2002993.75286588 259012.15364673
#Sta/Elev= 30
       0 1512.22    15.1 1502.67    17.5 1500.81    24.4 1493.93    28.4 1492.04
    36.3 1491.22    40.3 1488.95    48.3 1482.64    60.2 1470.29    64.7 1467.94
    74.1 1465.77    83.6 1462.05    88.6 1460.99   183.5 1457.28   187.4 1456.43
   189.8 1455.01   195.4 1449.93   199.4 1448.61   208.6 1448.43   216.3  1448.7
   220.4 1449.72   223.2 1451.51     228  1456.9   234.6  1467.6   239.1 1473.68
   253.7 1489.68     259 1494.09   269.5 1499.82   305.5 1514.96   323.3  1523.9
#Mann= 4 ,-1 , 0
       0      .1       0      80     .06       0   195.4    .045       0
   220.4      .1       0
#XS Ineff= 2 , 0
          181.68 1463.79
Permanent Ineff=
       F       F
Bank Sta=195.4,220.4
XS Rating Curve= 0 ,0
Exp/Cntr=0.3,0.1

Type RM Length L Ch R = 1 ,1360    ,188.2,186.1,182.5
XS GIS Cut Line= 4
2003036.49943716258639.6587908512002978.78697421258785.440468792
2002888.37302644258823.629145698  2002840.220653258890.332025794
#Sta/Elev= 30
       0 1501.22    12.5  1497.5    44.3 1486.32    50.6    1482    65.4 1468.13
    70.8 1464.97    73.3 1464.51    79.6 1465.23    86.6 1463.94   106.2 1463.59
   116.3 1461.69   121.9 1461.61     134 1459.83   184.3  1458.4   188.4 1456.95
   191.9 1454.55   201.8 1443.15   202.6 1442.44   206.2 1441.91   227.6 1441.48
   231.9  1441.6   238.2 1443.06   245.4 1444.88   248.9 1446.86     269  1462.1
   299.1 1488.11   317.9 1506.68   325.6 1512.38     332 1519.07   337.2 1525.41
#Mann= 4 ,-1 , 0
       0     .04       0  196.79      .1       0   201.8    .045       0
   238.2      .1       0
Bank Sta=201.8,238.2
XS Rating Curve= 0 ,0
Exp/Cntr=0.3,0.1

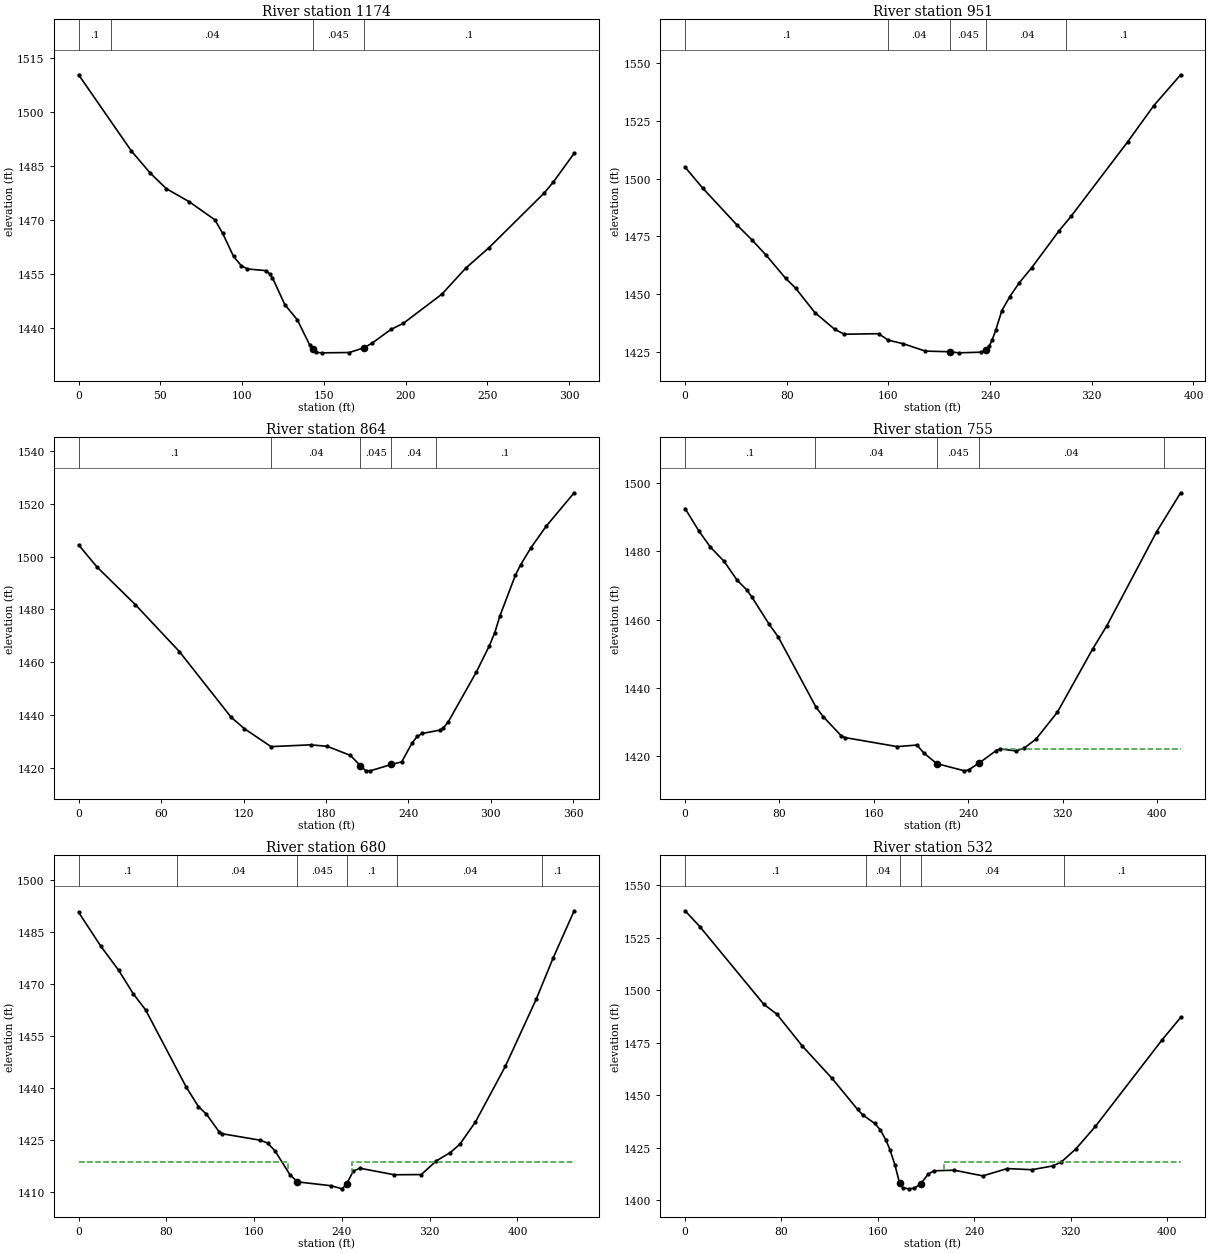
Type RM Length L Ch R = 1 ,1174    ,220.8,223,220
XS GIS Cut Line= 3
2002956.06711704258532.5059137372002909.49626193258603.729248985
2002722.01206631258714.827044652
#Sta/Elev= 30
       0 1510.45    32.2 1489.24    43.9 1482.99    53.6 1478.71    67.5 1475.09
    83.3 1470.03      88 1466.32    94.7 1459.85    99.4 1457.26   103.2 1456.32
   114.7 1455.85   116.8 1454.93   118.5  1453.9   126.1 1446.36   133.7 1442.17
   141.4 1435.02   143.2 1433.99   145.2 1433.05     149 1432.94   165.5 1433.03
   174.3 1434.32   179.5 1435.66   190.9 1439.45   198.6 1441.18   222.2 1449.33
   236.7 1456.55   250.9 1462.25   284.5 1477.41   290.1 1480.45     303 1488.57
#Mann= 4 ,-1 , 0
       0      .1       0      20     .04       0   143.2    .045       0
   174.3      .1       0
Bank Sta=143.2,174.3
XS Rating Curve= 0 ,0
Exp/Cntr=0.3,0.1

Type RM Length L Ch R = 1 ,951     ,80.3,87.1,83.3
XS GIS Cut Line= 2
2002899.12070148258353.9799195862002566.48637953258557.342917503
#Sta/Elev= 30
       0 1504.93    13.8 1495.91    40.7 1479.99    52.3 1473.65    63.8 1466.84
    79.2 1456.81    86.9 1452.65   102.2    1442   117.6 1434.87   125.3 1432.69
   152.2 1432.93   159.9 1430.12   171.5 1428.62     189  1425.4   208.1 1425.13
   215.3 1424.65     233 1424.94   237.1 1425.94   239.2 1427.48   241.5 1430.08
   244.5 1434.57   249.2  1442.9   255.5 1448.97     263    1455   272.6 1461.37
     294 1477.25   303.6 1483.62   348.4 1516.01   368.7  1531.5   389.9 1544.88
#Mann= 5 ,-1 , 0
       0      .1       0     160     .04       0   208.1    .045       0
   237.1     .04       0     300      .1       0
Bank Sta=208.1,237.1
XS Rating Curve= 0 ,0
Exp/Cntr=0.3,0.1

Type RM Length L Ch R = 1 ,864     ,95.2,109.2,129.1
XS GIS Cut Line= 2
2002869.25389586258288.4646779242002554.81303901258464.966857007
#Sta/Elev= 30
       0  1504.4    13.1 1496.18    41.2 1481.79    73.3 1463.98     111 1439.06
   120.7 1434.72     140 1427.94   168.9 1428.62   180.9 1428.05   197.8  1424.6
   204.9 1420.77   208.8 1418.84   212.2 1418.76   227.6 1421.18   235.1 1422.15
   242.6 1429.27   246.4 1431.83   250.1 1432.93   262.9 1434.19   265.3 1434.94
     269 1437.36   289.4  1456.2   298.9 1466.19   302.8 1471.13   306.6 1477.55
   317.9 1493.02   321.6 1496.83   329.2 1503.39   340.4  1511.6   360.6 1524.16
#Mann= 5 ,-1 , 0
       0      .1       0     140     .04       0   204.9    .045       0
   227.6     .04       0     260      .1       0
Bank Sta=204.9,227.6
XS Rating Curve= 0 ,0
Exp/Cntr(USF)=0,0
Exp/Cntr=0.5,0.3

Type RM Length L Ch R = 1 ,755     ,71.7,74.7,67.3
XS GIS Cut Line= 4
2002836.87187458258248.2699050952002721.92297644 258317.23924398
2002544.67919156258277.9341368732002469.03540053258349.869898936
#Sta/Elev= 30
       0  1492.6    11.8 1485.95    21.5 1481.26      33 1477.12    44.1 1471.57
    52.1 1468.78    56.4 1466.73    71.2 1458.65    78.9 1454.92   111.1  1434.2
   117.1  1431.5   132.4 1425.85   135.8 1425.34   179.7 1422.71   196.5 1423.16
   202.2 1420.86   213.3 1417.71   236.8 1415.59   240.2 1415.86   248.9  1417.8
   263.7 1421.55   267.1 1422.03   280.5 1421.44   287.2 1422.23   297.3 1424.86
   315.6 1432.84   345.3 1451.29   357.5 1458.22   399.6 1485.75     420 1497.23
#Mann= 5 ,-1 , 0
       0      .1       0     110     .04       0   213.3    .045       0
   248.9     .04       0   405.6      .1       0
#XS Ineff= 2 ,-1
       0     194    1422     269419.9893    1422
Permanent Ineff=
       F       F
Bank Sta=213.3,248.9
XS Rating Curve= 0 ,0
Exp/Cntr(USF)=0,0
Exp/Cntr=0.5,0.3

Type RM Length L Ch R = 1 ,680     ,174.3,148.6,121.6
XS GIS Cut Line= 4
2002813.14048916258196.3574994822002698.19159102258257.910780423
2002522.43101773258211.189615371 2002431.9551108 258317.23924398
#Sta/Elev= 30
       0 1490.58      20 1480.92    36.5 1473.89    49.8 1467.13      61 1462.53
    98.2 1440.23   109.2  1434.7   116.5  1432.5     128 1427.46   130.4  1426.9
   165.5 1425.02   172.3 1424.18   179.1 1421.91   192.7 1415.06   199.5 1413.03
     230 1411.93   240.2 1411.03   244.2  1412.4   250.4 1416.15   256.4 1416.96
   287.7 1415.08   312.3 1415.13     326 1419.06   338.8 1421.48   347.4 1423.82
   361.7 1430.27   388.9 1446.23   417.3 1465.72   432.4 1477.33   451.7 1491.01
#Mann= 6 ,-1 , 0
       0      .1       0      90     .04       0   199.5    .045       0
   244.2      .1       0  290.39     .04       0  422.26      .1       0
#XS Ineff= 2 ,-1
       0   190.9  1418.8   249.2451.6565  1418.8
Permanent Ineff=
       F       F
Bank Sta=199.5,244.2
XS Rating Curve= 0 ,0
Exp/Cntr(USF)=0,0
Exp/Cntr=0.5,0.3

Type RM Length L Ch R = 1 ,532     ,154.9,151.5,147.8
XS GIS Cut Line= 3
2002605.24223303257944.3595892922002547.39698106258087.489507624
2002396.10939899258295.139130074
#Sta/Elev= 30
       0 1537.91    12.3 1530.31    65.4 1493.29      76 1488.72    97.2 1473.49
     122    1458   143.2 1443.18   147.4 1440.64   157.3 1436.56   161.9 1433.58
   166.7  1428.6     170 1424.03   174.1 1416.88   178.1  1407.9   180.8 1405.91
   185.5 1405.35   190.3 1405.64   195.5 1407.76   201.9 1412.42   206.7 1413.95
   223.4 1414.24   247.1 1411.52   267.4 1415.02   287.7 1414.47   305.2 1416.27
   312.3 1418.17   324.3 1424.35   340.5 1435.08   396.1 1476.51   411.3 1487.04
#Mann= 5 ,-1 , 0
       0      .1       0     150     .04       0   178.1    .045       0
   195.5     .04       0  314.38      .1       0
#XS Ineff= 2 , 0
                             215            1418
Permanent Ineff=
       F       F
Bank Sta=178.1,195.5
XS Rating Curve= 0 ,0
Exp/Cntr(USF)=0,0
Exp/Cntr=0.3,0.1

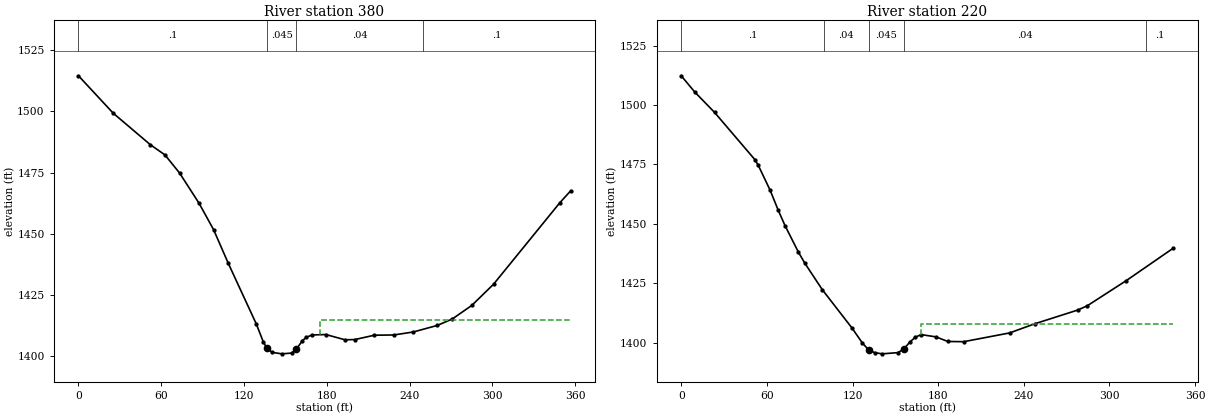
Type RM Length L Ch R = 1 ,380     ,154.9,160.8,163.9
XS GIS Cut Line= 2
 2002445.1238279257913.884686034  2002313.862043 258245.50803189
#Sta/Elev= 30
       0 1514.53    25.2 1499.25    52.1  1486.4    62.7 1482.23    73.3 1474.83
    87.4  1462.5      98 1451.65   108.6 1437.96   128.9 1413.23   133.9 1406.02
   136.4 1403.45   140.3 1401.66   147.4 1401.05   154.4 1401.36     158 1403.04
   162.3 1406.41     165 1407.77   169.3 1408.76   179.4 1408.92   193.2 1406.78
   200.3 1406.88   214.4 1408.65   228.5 1408.75   242.6 1409.96   260.2 1412.67
   270.9 1415.27     285 1420.78   300.8 1429.44   348.8 1462.67   356.7 1467.57
#Mann= 4 ,-1 , 0
       0      .1       0   136.4    .045       0     158     .04       0
     250      .1       0
#XS Ineff= 2 , 0
                             175            1415
Permanent Ineff=
       F       F
Bank Sta=136.4,158
XS Rating Curve= 0 ,0
Exp/Cntr=0.3,0.1

Type RM Length L Ch R = 1 ,220     ,219.5,219.5,219.5
XS GIS Cut Line= 3
2002331.80331068257869.4223077262002180.73546366258075.423917302
2002156.93083322 258161.48681197
#Sta/Elev= 30
       0 1512.28     9.4  1505.5    23.4 1496.84    51.6    1477      54 1474.58
    62.3 1464.11      68 1455.66    72.7 1449.27    82.1 1438.08    86.7 1433.33
    98.9 1422.24   119.7 1406.12   126.7 1400.04   131.3 1396.93   135.5 1395.82
   140.8 1395.31   151.8 1395.82   155.9 1397.31     160 1400.16     164 1402.33
   168.1  1403.4   178.4 1402.45   186.8 1400.51   197.9 1400.42     230  1404.1
   247.8 1407.98   277.7 1413.71   284.5 1415.54   311.9 1426.16   344.8  1439.8
#Mann= 5 ,-1 , 0
       0      .1       0     100     .04       0   131.3    .045       0
   155.9     .04       0  325.46      .1       0
#XS Ineff= 2 , 0
                             168            1408
Permanent Ineff=
       F       F
Bank Sta=131.3,155.9
XS Rating Curve= 0 ,0
Exp/Cntr(USF)=0,0
Exp/Cntr=0.3,0.1