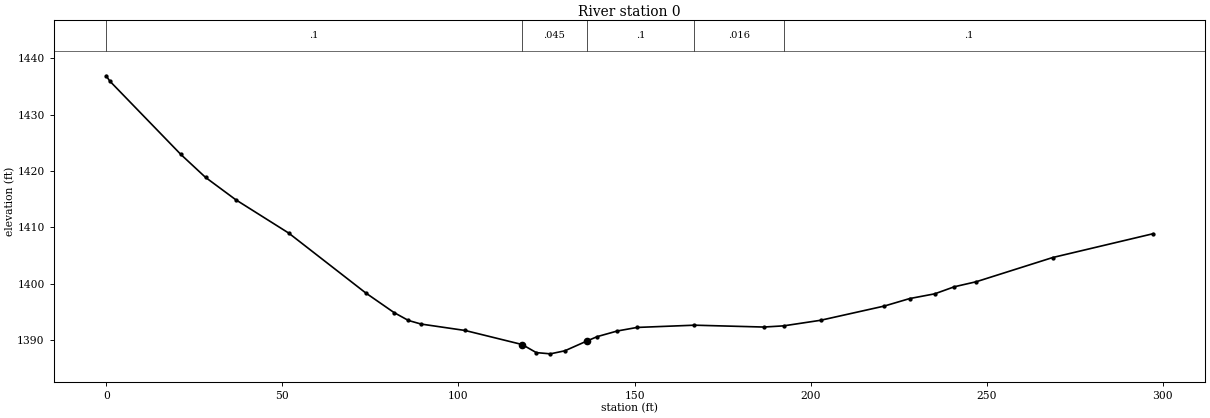
HEC-RAS study BRKSBR_A.prj: BRKSBR_A

--- BRKSBR_A.g01 (geometry) --- (continued)

Type RM Length L Ch R = 1 ,0       ,36.1,27.1,15.1
XS GIS Cut Line= 4
2001995.75198199257820.4197445882002017.18539399257850.362449737
 2002138.2625121258019.2337192282002160.32793774258067.005289432
#Sta/Elev= 30
       0 1436.93       1    1436    21.2 1422.95    28.2 1418.88    36.8  1414.9
    51.8 1408.99    73.7 1398.34    81.7 1394.87    85.8 1393.46    89.4 1392.82
   101.9 1391.68   118.1 1389.18   122.1 1387.75   126.1 1387.53   130.2 1388.07
   136.4 1389.79   139.4 1390.59   145.1 1391.59   150.7 1392.22     167 1392.62
   186.7 1392.29   192.3  1392.5   202.8 1393.49   220.9 1396.02   228.1 1397.35
   235.2 1398.19   240.8 1399.45     247 1400.34   268.7 1404.64   297.2 1408.87
#Mann= 5 ,-1 , 0
       0      .1       0   118.1    .045       0   136.4      .1       0
     167    .016       0   192.3      .1       0
Bank Sta=118.1,136.4
XS Rating Curve= 0 ,0
Exp/Cntr(USF)=0,0
Exp/Cntr=0.5,0.3
LCMann Table=0

Chan Stop Cuts=-1
Use User Specified Reach Order=0
Composite Channel Slope=5